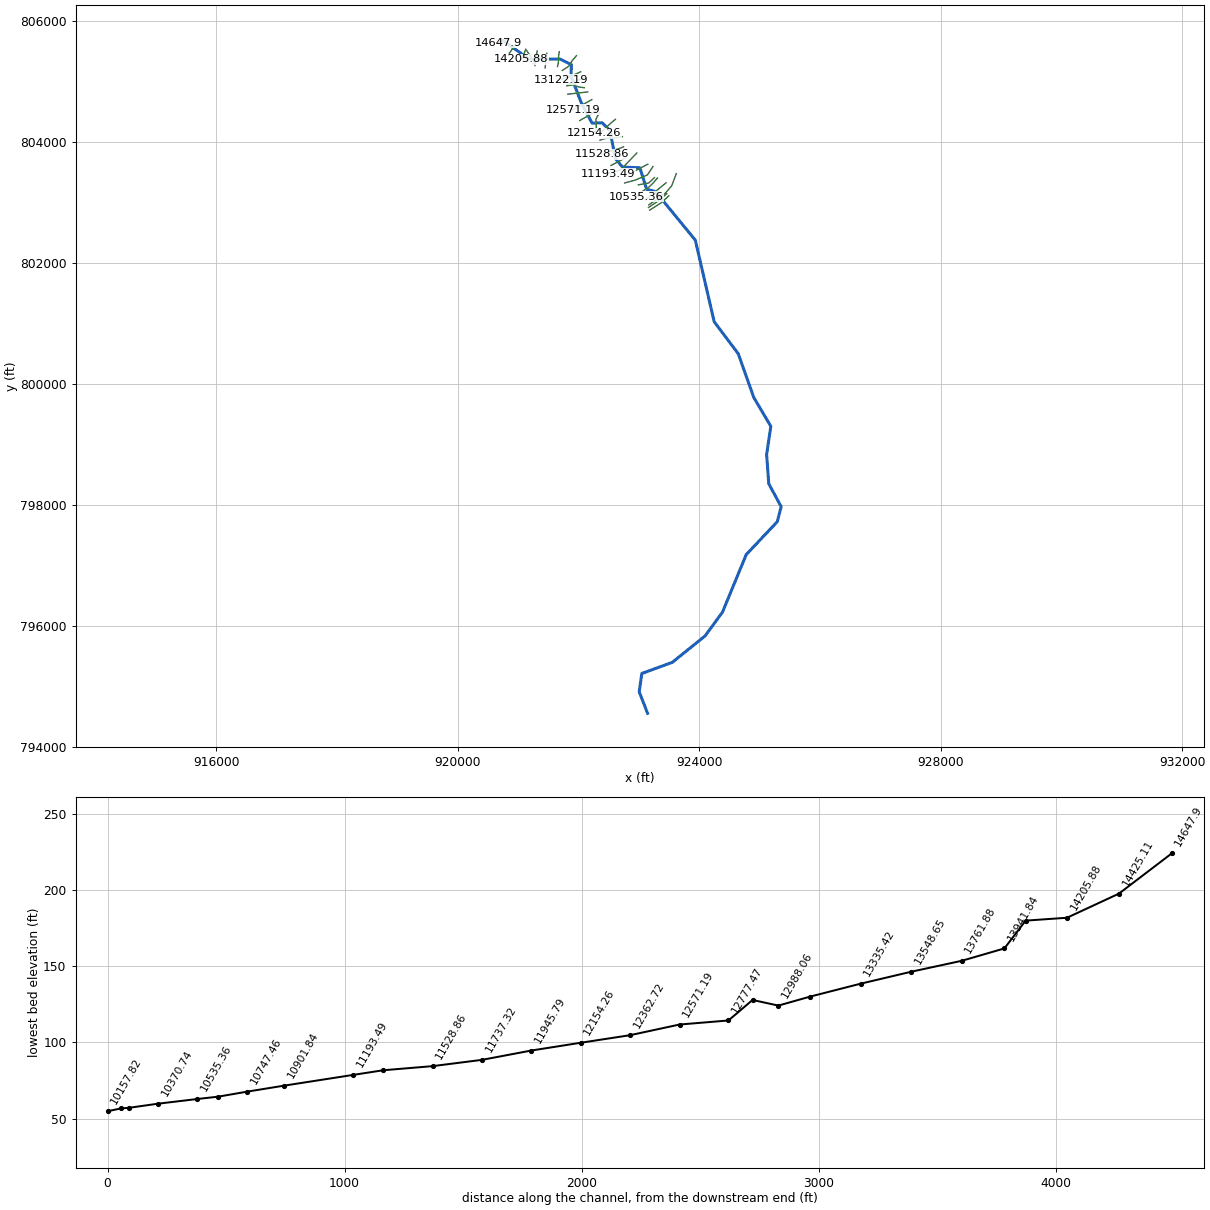
--- 13263_ras.prj (project) ---

Proj Title=13263
Current Plan=p01
Default Exp/Contr=0.3,0.1
English Units
Geom File=g01
Flow File=f01
Plan File=p01
Y Axis Title=Elevation
X Axis Title(PF)=Main Channel Distance
X Axis Title(XS)=Station
BEGIN DESCRIPTION:
RFD model 13263 exported to HEC-RAS
END DESCRIPTION:

--- 13263_ras.p01 (plan) ---

Plan Title=Plan 01
Program Version=4.10
Short Identifier=Plan 01
Geom File=g01
Flow File=f01
Subcritical Flow
Calc Critical at every XS
Secant Critical Depth

--- 13263_ras.f01 (steady flow) ---

Flow Title=Flow 01
Program Version=5.01
Number of Profiles= 6
Profile Names=10yr,25yr,50yr,100yr,100plus,500yr
River Rch & RM=13263,43, 14647.9
  193.48  295.62  387.28  465.88  680.19 1106.16
River Rch & RM=13263,43,14205.88
  199.25   304.9  399.83  481.41  702.86 1139.96
River Rch & RM=13263,43,14031.37
  268.48  413.11  543.84  656.83  958.97 1498.33
River Rch & RM=13263,43,13761.88
  279.65  431.04  568.11  686.83 1002.77 1560.36
River Rch & RM=13263,43,13548.65
  285.71   440.8  581.34  703.21 1026.68 1594.16
River Rch & RM=13263,43,13335.42
  414.89  646.64  858.78 1044.87 1525.51 2268.21
River Rch & RM=13263,43,13122.19
   419.6  654.29  869.22 1057.86 1544.48  2293.8
River Rch & RM=13263,43,12879.18
  422.28  658.65  875.17 1065.27 1555.29 2308.38
River Rch & RM=13263,43,12777.47
   427.3  666.81  886.31 1079.13 1575.53  2335.6
River Rch & RM=13263,43,12571.19
  431.93  674.36  896.62 1091.99  1594.3  2360.9
River Rch & RM=13263,43,12362.72
  444.42  694.87   924.8 1127.27 1645.81 2430.83
River Rch & RM=13263,43,12154.26
  450.27  704.58  938.22 1144.16 1670.48 2464.61
River Rch & RM=13263,43,11945.79
  451.54  706.66  941.09 1147.75 1675.72  2471.7
River Rch & RM=13263,43,11737.32
  457.28  716.38  954.68 1165.04 1700.97 2507.02
River Rch & RM=13263,43,11528.86
  464.94  729.09  972.24 1187.13 1733.21  2550.9
River Rch & RM=13263,43,11320.39
  468.17   734.5  979.77 1196.67 1747.13 2570.12
River Rch & RM=13263,43,11193.49
  468.97  735.89  981.73 1199.19 1750.82 2575.35
River Rch & RM=13263,43,10901.84
  503.29  793.58 1062.11 1301.07 1899.57 2779.61
River Rch & RM=13263,43,10747.46
  510.38  805.66 1079.09 1322.75 1931.21 2823.45
River Rch & RM=13263,43,10624.76
  511.41  807.45 1081.62 1326.01 1935.97 2830.17
River Rch & RM=13263,43,10535.36
  517.56  818.12 1096.78 1345.53 1964.47 2870.36
River Rch & RM=13263,43,10370.74
  781.03 1236.55 1660.05 2037.83 2975.24  4103.5
River Rch & RM=13263,43,10157.82
  782.43 1238.99 1663.52 2042.31 2981.78 4112.21
River Rch & RM=13263,43,10112.64
  783.13 1240.21 1665.26 2044.55 2985.05 4116.56
River Rch & RM=13263,43,9840.443
  794.56 1259.83 1692.97 2080.05 3036.87 4184.47
River Rch & RM=13263,43,9676.287
  796.66 1263.48 1698.16 2086.74 3046.64 4197.42
River Rch & RM=13263,43,  9484.7
  799.43 1268.31 1705.04 2095.63 3059.61 4214.67
River Rch & RM=13263,43, 9347.76
  805.23 1278.54 1719.69 2114.63 3087.36 4251.95
River Rch & RM=13263,43, 9236.38
  820.45 1304.91 1757.12 2162.81 3157.71 4344.59
River Rch & RM=13263,43, 9001.63
  823.33 1309.98 1764.39 2172.25 3171.48 4363.02
River Rch & RM=13263,43,8789.315
  832.66 1326.26  1787.6 2202.23 3215.25 4420.96
River Rch & RM=13263,43,8314.529
  843.77  1346.4 1816.94  2240.8 3271.57 4498.22
River Rch & RM=13263,43, 7604.32
  898.38 1444.63 1959.43  2427.6  3544.3 4867.55
River Rch & RM=13263,43,6861.317
  910.86 1468.15 1994.43 2474.42 3612.66 4963.55
River Rch & RM=13263,43,5943.595
   935.5    1515 2064.48 2568.53 3750.05 5157.37
River Rch & RM=13263,43,5414.332
  940.56 1524.62 2078.86 2587.86 3778.27 5197.11
Boundary for River Rch & Prof#=13263,43,1
Up Type= 0
Dn Type= 2
Boundary for River Rch & Prof#=13263,43,2
Up Type= 0
Dn Type= 2
Boundary for River Rch & Prof#=13263,43,2
Up Type= 0
Dn Type= 2
Boundary for River Rch & Prof#=13263,43,2
Up Type= 0
Dn Type= 2
Boundary for River Rch & Prof#=13263,43,2
Up Type= 0
Dn Type= 2
Boundary for River Rch & Prof#=13263,43,2
Up Type= 0
Dn Type= 2

--- 13263_ras.g01 (geometry) ---

Geom Title=13263
Program Version=4.10

River Reach=13263,43
Reach XY= 30
920752.371411771805675.663032547921182.430366546805370.771316051
921696.319255441805369.382427201921884.721447825805276.515020877
921878.999676406805083.980021536922053.171071082804637.060660318
922227.174491853804309.504094049922395.028324664804316.338997036
922523.402588755804186.049093857922613.099455386 803726.80304496
 922731.04147765803583.965760544923019.328983128803571.638267964
923131.182536781803217.079952776923278.437311023803178.410204977
923937.291477621802376.326871663924249.791477621801027.368538335
 924648.22897765800498.722705022924905.987224191799773.932485089
925188.105279714799297.586998984925118.529870629798829.662724063
925154.338786691798346.865282997925359.615088463797968.958557427
925294.963786691797720.129171938924781.074897796797176.726394132
 924387.43216756796224.823508799924100.311896145795832.648610875
923557.376981139795395.302783027923051.734620005 795210.84097746
923008.331842244794907.021533057923147.220731139794551.118755266

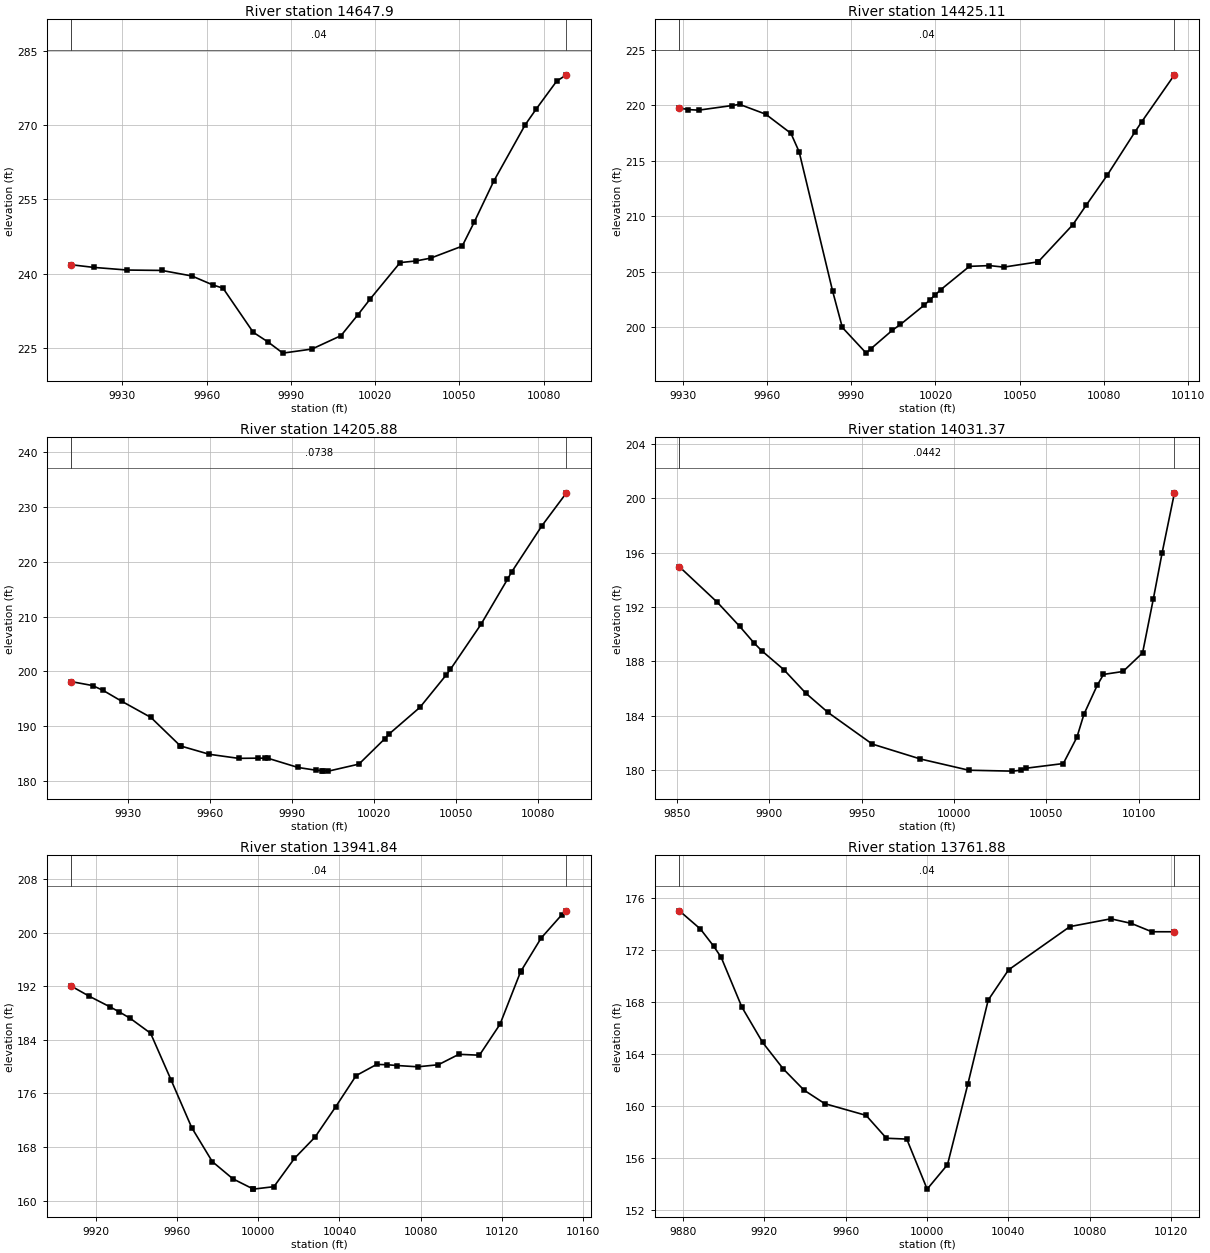
Type RM Length L Ch R = 1 , 14647.9,222.785300,222.785300,222.785300
XS GIS Cut Line= 6
920831.634950977805712.247879774920808.357349631805697.018885635
920788.422183689805686.622647702920770.133714067 805679.44829264
920719.715222899805664.385615665920671.897438411805640.128604806
#Sta/Elev= 24
9911.874241.84119919.803241.31229931.753240.77849944.057240.70049954.756239.5807
9962.174237.7892 9965.85237.12249976.592 228.236 9981.82226.30259987.143224.0376
9997.512224.861710007.83227.558810013.91 231.80410018.28234.983110028.88242.2809
10034.48242.605310039.77243.182210050.98245.596410055.23250.4004 10062.2258.6771
10073.41270.048610077.33273.226410084.62278.8451 10088.1280.1138
#Mann= 3 , 0 , 0
9911.874    0.04       09911.874    0.04       0 10088.1    0.04       0
#XS Ineff= 2 , 0
       0                               0
Bank Sta=9911.874,10088.1
Exp/Cntr=0.3,0.1

Type RM Length L Ch R = 1 ,14425.11,219.233200,219.233200,219.233200
XS GIS Cut Line= 5
920956.702274585805610.722402846920919.415260482805553.556971351
920908.484748091805538.132343523 920907.29739412 805536.52293663
920856.853675092805465.443392938
#Sta/Elev= 29
9928.794 219.773 9931.91219.62639935.626219.57319947.565219.99189950.214220.0967
9959.504219.21389968.518 217.4819971.444215.81219983.383203.22389986.823199.9648
9995.322197.64799997.045198.054710004.68199.721510007.53200.236310015.95201.9703
10017.95202.437510019.82 202.88510021.92203.382410032.08205.4782 10039.2205.5469
10044.34205.409910056.48 205.882 10056.6205.890410068.87209.222810073.76211.0276
10081.13213.688910091.03217.602310093.39218.503410105.11222.7622
#Mann= 3 , 0 , 0
9928.794    0.04       09928.794    0.04       010105.11    0.04       0
#XS Ineff= 2 , 0
       0                               0
Bank Sta=9928.794,10105.11
Exp/Cntr=0.3,0.1

Type RM Length L Ch R = 1 ,14205.88,174.509400,174.509400,174.509400
XS GIS Cut Line= 5
921129.100041368805532.231914161921104.094665962 805465.79096599
921096.147789962 805449.00951894921095.252724853805447.220983659
921055.394505686805366.984828288
#Sta/Elev= 28
9909.441 198.1429917.169197.42959921.081196.53549927.853 194.5649938.538191.6103
9949.223186.46199949.472186.40219959.908184.89429970.592184.15429977.862184.1921
9980.432184.18349981.307184.17799992.372182.4903    9999181.9835   10001181.9139
10001.57181.900910003.48181.824910014.65183.106510024.05 187.69810025.81188.6484
10036.98193.460810046.52199.321910048.14200.392810059.31208.5912   10069216.8015
10070.48218.099510081.64226.591410090.59232.5725
#Mann= 3 , 0 , 0
9909.441  0.0738       09909.441  0.0738       010090.59  0.0738       0
#XS Ineff= 2 , 0
       0                               0
Bank Sta=9909.441,10090.59
Exp/Cntr=0.3,0.1

Type RM Length L Ch R = 1 ,14031.37,89.529700,89.529700,89.529700
XS GIS Cut Line= 5
 921142.74358991805512.212654352921205.677617688805416.726543241
921251.250534355805368.983487686921268.611645466805338.601543241
921251.250534355805288.688348797
#Sta/Elev= 24
9851.215 194.964 9871.83192.34189883.807190.59269891.659189.35919895.784188.7938
 9907.76187.40179919.737185.66219931.714184.25249955.667181.92749981.787 180.828
10008.04180.001610031.58179.935610036.17179.999110039.14180.1519 10059.2180.4933
10066.57182.426310070.38184.116810077.56186.241810080.97187.047410091.56 187.264
10102.15188.6298   10108192.617310112.73195.984510119.42200.4025
#Mann= 3 , 0 , 0
9851.215  0.0442       09851.215  0.0442       010119.42  0.0442       0
#XS Ineff= 2 , 0
       0                10028.29       0
Bank Sta=9851.215,10119.42
Exp/Cntr=0.3,0.1

Type RM Length L Ch R = 1 ,13941.84,179.960900,179.960900,179.960900
XS GIS Cut Line= 2
 921318.52483991805503.532098797921281.632478799 805262.64668213
#Sta/Elev= 30
 9908.05192.00969916.682190.53559926.798188.96199931.334188.21869936.915187.2263
9947.032184.98059957.148177.98179967.265170.89099977.381165.82079987.498163.2517
9997.389161.74169997.615161.705210007.73162.071510017.85166.297710027.96169.4708
10038.08173.9749 10048.2178.659110058.31180.331410063.44180.281410068.43180.1642
10078.55179.973410088.66180.280110098.78181.8375 10108.9181.705810119.01186.3174
10129.13194.1522 10129.5  194.3410139.25 199.19110149.36202.648510151.74203.2659
#Mann= 3 , 0 , 0
 9908.05    0.04       0 9908.05    0.04       010151.74    0.04       0
#XS Ineff= 2 , 0
       0                               0
Bank Sta=9908.05,10151.74
Exp/Cntr=0.3,0.1

Type RM Length L Ch R = 1 ,13761.88,213.229500,213.229500,213.229500
XS GIS Cut Line= 6
921478.157524923 805465.17709385921461.231675579805376.493612647
921459.930091959805346.103435125921460.054849185805344.107330009
921458.412235727805295.544664741921449.721814393805223.947294025
#Sta/Elev= 22
9878.298174.99279888.659173.5884 9895.14172.27439898.839171.4139 9909.02167.5855
  9919.2164.87079929.381162.82929939.561161.20019949.742160.15969970.077159.2575
9980.086 157.4979990.095157.432610000.11153.582510010.11155.463910020.12161.6572
10030.12168.123210040.13170.450710070.29173.778510090.43174.378610100.51174.0252
10110.58 173.38210121.71173.3815
#Mann= 3 , 0 , 0
9878.298    0.04       09878.298    0.04       010121.71    0.04       0
#XS Ineff= 2 , 0
       0                               0
Bank Sta=9878.298,10121.71
Exp/Cntr=0.3,0.1

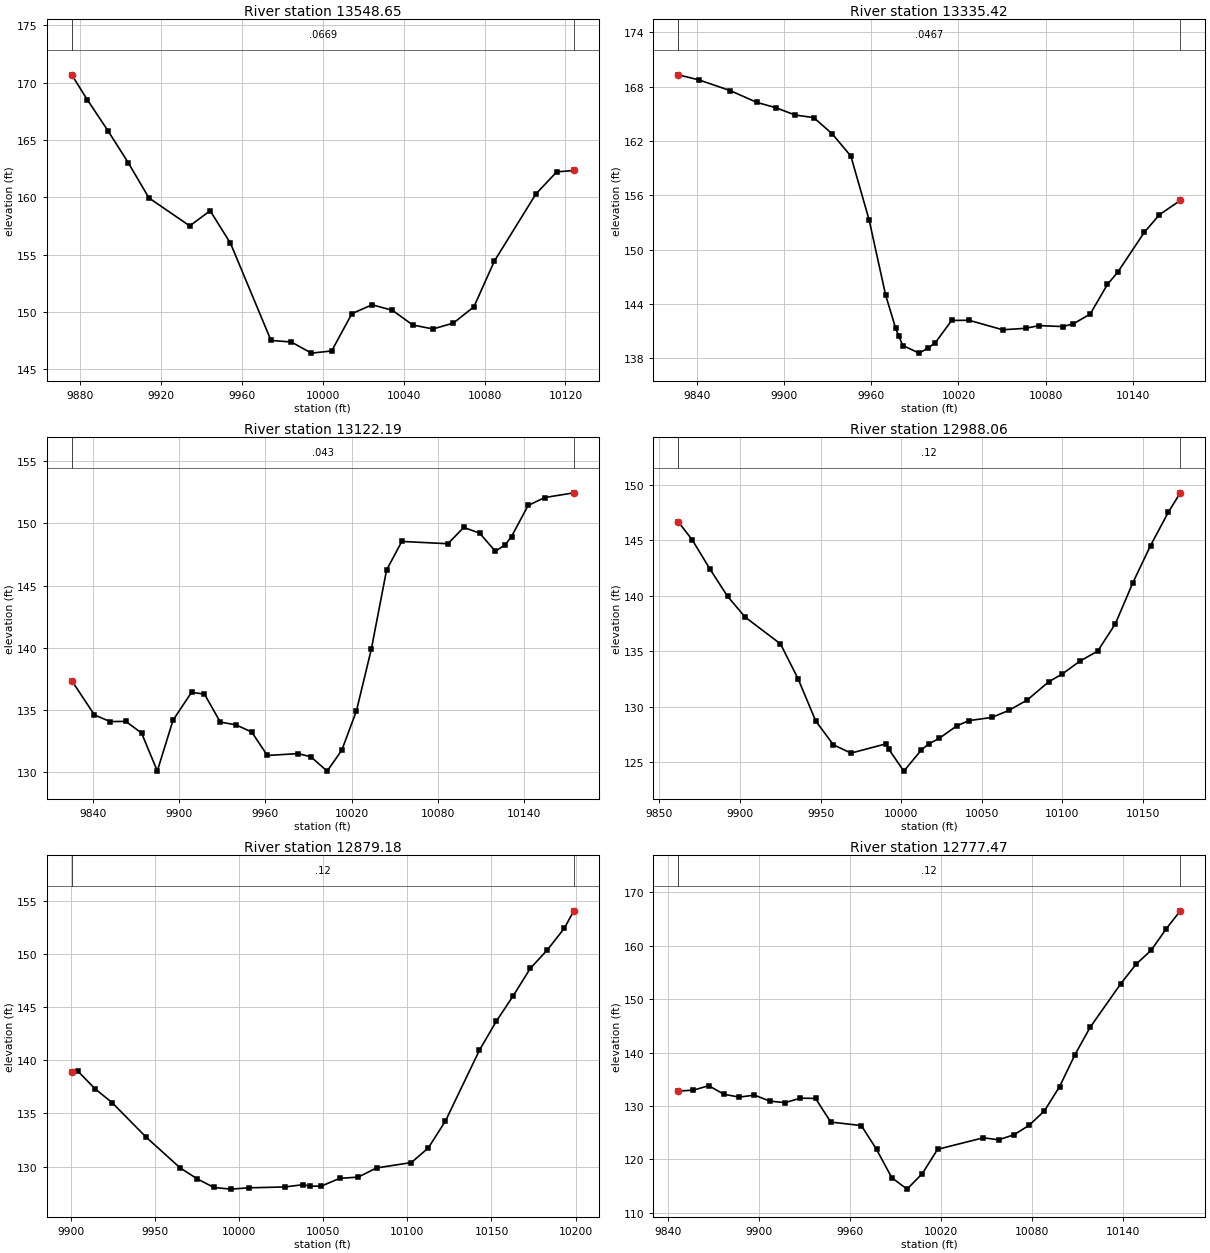
Type RM Length L Ch R = 1 ,13548.65,213.229600,213.229600,213.229600
XS GIS Cut Line= 6
921684.656312119805492.524704744921672.795227399805417.701634377
921671.136776367805340.706136858 921669.00284631805314.539685606
921663.711669161  805282.0441726921655.151797809805246.775621615
#Sta/Elev= 23
9875.843170.68569883.497168.52119893.668165.82749903.839163.0005 9914.01159.9454
9934.201157.50789944.278158.8298 9954.34155.99269974.376 147.5169984.382147.3824
9994.382146.409710004.38   146.610014.38149.852410024.38 150.627 10034.4150.1467
10044.43148.867710054.47148.515410064.59149.033310074.73150.451310084.86154.4423
10105.39160.294710115.68162.219710124.15162.3403
#Mann= 3 , 0 , 0
9875.843  0.0669       09875.843  0.0669       010124.15  0.0669       0
#XS Ineff= 2 , 0
       0                               0
Bank Sta=9875.843,10124.15
Exp/Cntr=0.3,0.1

Type RM Length L Ch R = 1 ,13335.42,213.229500,213.229500,213.229500
XS GIS Cut Line= 6
921968.584268324805425.672185921921891.773010511805334.826324929
921855.399763687805270.920901998921844.696331057805256.572691446
921822.841653357805238.483908096921733.211166831805181.004370248
#Sta/Elev= 30
 9827.25169.3075 9841.44168.75099863.036167.56379881.327166.26299894.623 165.666
9907.698164.86589920.474164.5865 9933.25162.77849946.026160.3298 9958.59153.2687
9969.965144.96359976.812 141.3299978.831140.50329981.737139.41469992.964138.5744
    9999139.121710004.15139.730410015.34142.180110027.28142.204610050.39141.1555
10066.17141.3123 10075.4141.612610091.72141.509110098.94141.799510110.68 142.889
10122.49146.154710129.63147.516410148.03151.947410158.35153.865810172.67155.4326
#Mann= 3 , 0 , 0
 9827.25  0.0467       0 9827.25  0.0467       010172.67  0.0467       0
#XS Ineff= 2 , 0
       0                               0
Bank Sta=9827.25,10172.67
Exp/Cntr=0.3,0.1

Type RM Length L Ch R = 1 ,13122.19,134.127900,134.127900,134.127900
XS GIS Cut Line= 6
922039.391979886 805158.65579896921908.484368093805100.811793845
921849.971242008805088.498746965921802.076712433 805072.02881401
921758.758274968805052.038532472921717.421928099 805028.30270455
#Sta/Elev= 30
9825.456137.3641 9841.19134.61279852.123134.07829863.056134.09269873.988133.1532
9884.921130.10959895.854134.19219908.727136.43079917.719136.28219928.652 134.042
9939.585133.81559950.518133.2421 9961.45131.35519982.642131.50639991.606 131.255
10002.98130.099210013.16131.781810023.34134.936410033.72139.909910044.29146.2466
10054.87148.5466 10086.9148.363510097.92149.667410108.93149.220510119.94147.7532
10126.82148.284410131.15148.938710142.68151.434610154.22152.071710174.48152.4509
#Mann= 3 , 0 , 0
9825.456   0.043       09825.456   0.043       010174.48   0.043       0
#XS Ineff= 2 , 0
       0                               0
Bank Sta=9825.456,10174.48
Exp/Cntr=0.3,0.1

Type RM Length L Ch R = 1 ,12988.06,108.884800,108.884800,108.884800
XS GIS Cut Line= 2
 922103.01877519805067.665278978921818.115012503804942.099790863
#Sta/Elev= 30
9861.759146.65899870.522145.0207 9881.45142.39619892.378139.94069903.306138.0675
9925.163 135.6619936.091132.51069947.019128.71549957.947126.57219968.875125.8183
9990.732126.65729992.346126.166710001.66124.194810012.59126.114110017.14126.6497
10023.52 127.14210034.44128.268310041.94128.7448 10056.3129.035310066.73129.6659
10078.16130.601310091.53132.247910100.01132.958910110.94134.115510121.87 135.012
 10132.8137.461910143.73141.191810154.65144.522810165.58147.504410173.11149.2754
#Mann= 3 , 0 , 0
9861.759    0.12       09861.759    0.12       010173.11    0.12       0
#XS Ineff= 2 , 0
       0                               0
Bank Sta=9861.759,10173.11
Exp/Cntr=0.3,0.1

Type RM Length L Ch R = 1 ,12879.18,101.705900,101.705900,101.705900
XS GIS Cut Line= 5
922098.688930772804895.337471152922000.834446932804909.192973289
921963.597784939804923.914444309921919.433371878 804943.83172863
921809.455323668804927.378319843
#Sta/Elev= 27
9900.448138.89879904.174138.96429914.274137.31859924.373136.02849944.573132.7873
9964.772129.90129974.872128.87129984.972128.04239995.072127.888810005.55128.0103
10027.06128.092710037.81128.302310041.96128.171610048.75128.165710059.72128.9017
10070.69129.015910081.66129.879110102.36130.387210112.47 131.76710122.58 134.277
10142.81 140.93710152.92143.680210163.03146.085710173.14148.651710183.25150.3771
10193.36152.423410198.97154.0478
#Mann= 3 , 0 , 0
9900.448    0.12       09900.448    0.12       010198.97    0.12       0
#XS Ineff= 2 , 0
       0                               0
Bank Sta=9900.448,10198.97
Exp/Cntr=0.3,0.1

Type RM Length L Ch R = 1 ,12777.47,206.281400,206.281400,206.281400
XS GIS Cut Line= 2
922154.976908203804826.059960468921825.908732455804788.823298476
#Sta/Elev= 30
9846.441132.79119856.482132.96279866.546133.79219876.609132.18029886.673 131.657
9896.737132.02669906.801 130.9149916.865130.61099926.928131.45829936.992131.4137
9947.056126.98099967.184 126.3349977.248121.86939987.311116.56429997.375114.4325
10007.44117.3369 10017.5121.883110047.69124.041510057.76 123.66810067.82124.5938
10077.89126.379710087.95129.069810098.01133.634710108.08139.577110118.14144.7218
10138.27152.851110148.33156.4952 10158.4159.144210168.46163.211710177.61166.5221
#Mann= 3 , 0 , 0
9846.441    0.12       09846.441    0.12       010177.61    0.12       0
#XS Ineff= 2 , 0
       0                               0
Bank Sta=9846.441,10177.61
Exp/Cntr=0.3,0.1

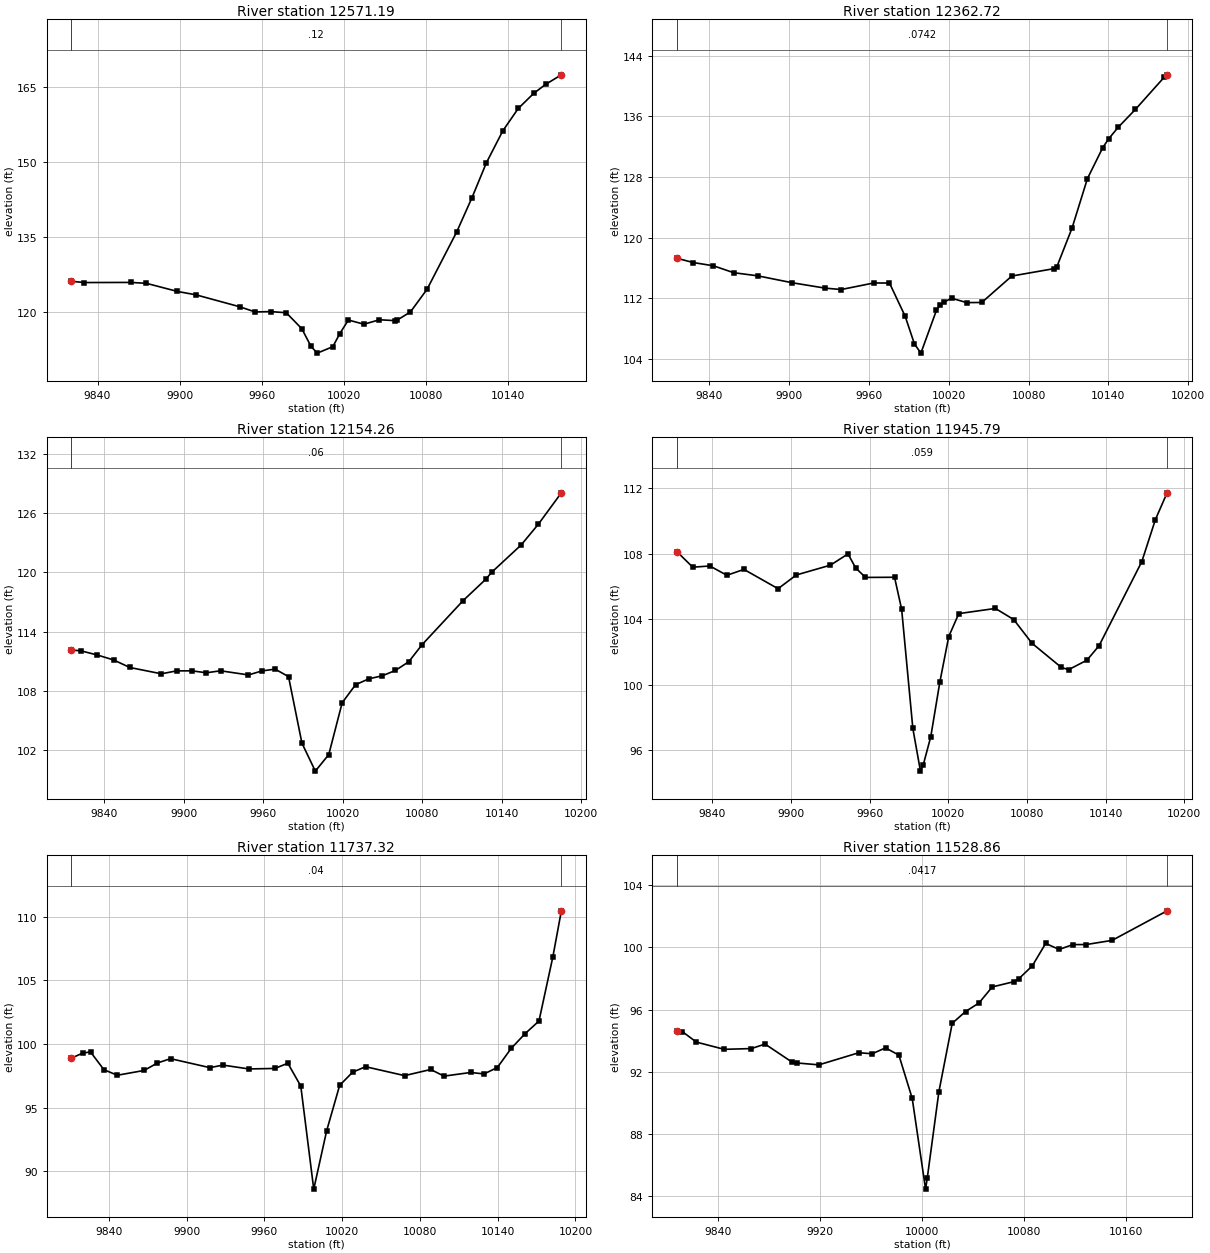
Type RM Length L Ch R = 1 ,12571.19,208.466600,208.466600,208.466600
XS GIS Cut Line= 5
922223.417908773804698.349041696922066.551206448 804613.66756844
922064.779474038804612.739686839922017.442489606804587.109312016
921907.035796329804529.709890236
#Sta/Elev= 30
9820.736126.13889830.302 125.8779864.394125.90359875.758125.72169898.486124.0981
9911.991123.42519943.943121.04559955.307120.00199966.671120.07269978.035119.8481
9989.399 116.6599996.195113.103810000.75111.773310012.12113.067710017.26115.6919
10023.49118.390710034.86117.549510046.24118.440810057.58118.2671 10059.4118.4144
10068.85119.992110081.08124.552710102.67135.968710113.94142.867910124.44149.8137
10136.48156.216310147.75160.669410159.02163.6777 10167.8165.488510179.27167.3898
#Mann= 3 , 0 , 0
9820.736    0.12       09820.736    0.12       010179.27    0.12       0
#XS Ineff= 2 , 0
       0                               0
Bank Sta=9820.736,10179.27
Exp/Cntr=0.3,0.1

Type RM Length L Ch R = 1 ,12362.72,208.466600,208.466600,208.466600
XS GIS Cut Line= 6
922330.542433602804553.088532488922271.900596196 804501.70567107
922222.964244589804466.122519578922170.037926179804433.450267067
922086.551462301804389.619709102922023.105590337804353.179893502
#Sta/Elev= 30
9815.948117.28489828.221116.72039843.395116.29169858.569115.3833  9876.5114.9736
9902.448114.06159927.176113.35119939.327113.1636 9963.81114.03019975.599114.0187
9987.387109.63519994.312106.00839999.176104.784410010.85110.4177 10013.6111.1278
10016.62 111.52310022.31 112.01610033.61111.4414 10044.9111.459510067.49114.9437
10099.34 115.92310101.37116.1967 10112.7 121.26310124.24127.775410135.77131.8636
10140.27133.0411 10147.3134.531510160.35136.9122 10181.9141.138510184.08141.4565
#Mann= 3 , 0 , 0
9815.948  0.0742       09815.948  0.0742       010184.08  0.0742       0
#XS Ineff= 2 , 0
       0                               0
Bank Sta=9815.948,10184.08
Exp/Cntr=0.3,0.1

Type RM Length L Ch R = 1 ,12154.26,208.466600,208.466600,208.466600
XS GIS Cut Line= 6
922354.996046374804480.882878752922314.989694929804423.249756434
922291.802819069804373.892392089922297.304554775804235.094080417
922283.687262436804189.016944486 922255.69272668 804139.27863548
#Sta/Elev= 30
9814.907112.11539822.208112.04129834.619111.61489847.031111.10799859.175110.3461
9883.009109.70469894.505110.00029905.913110.00729917.029109.81069927.786110.0093
9948.814109.58949958.935109.99539968.948110.17959979.061109.41769989.175102.6635
9999.29199.8187510009.44101.494510019.57106.7645 10029.7108.5982 10039.8 109.199
10049.81109.499710059.81110.046410069.86110.930210079.92112.662510110.93 117.142
10127.96119.300210132.43120.010310154.72122.788410167.64124.884410185.11128.0872
#Mann= 3 , 0 , 0
9814.907    0.06       09814.907    0.06       010185.11    0.06       0
#XS Ineff= 2 , 0
       0                10036.43       0
Bank Sta=9814.907,10185.11
Exp/Cntr=0.3,0.1

Type RM Length L Ch R = 1 ,11945.79,208.466600,208.466600,208.466600
XS GIS Cut Line= 6
 922614.30393964804373.458624966922552.860861754804322.377609533
922494.054767037804270.408001989922474.886178959804250.726179866
922458.012883166804232.470289443922341.190040366804118.791639183
#Sta/Elev= 30
9813.144108.12899825.243107.17949838.247107.25329851.252 106.6859864.256107.0446
9890.265105.86479904.188106.70339930.228107.30499943.574107.99039949.491107.1273
9956.919106.55419979.075106.56429984.504104.60259993.03497.323069998.83794.71781
   1000195.11099 10006.796.8211110013.64100.1726 10020.4102.940510028.07104.3428
10055.98104.659310069.93103.980410083.88102.531110106.27101.053710111.79100.9164
10125.74101.497210134.95102.3733 10167.6107.520910177.97110.091710186.87111.7236
#Mann= 3 , 0 , 0
9813.144   0.059       09813.144   0.059       010186.87   0.059       0
#XS Ineff= 2 , 0
       0                10040.41       0
Bank Sta=9813.144,10186.87
Exp/Cntr=0.3,0.1

Type RM Length L Ch R = 1 ,11737.32,208.466600,208.466600,208.466600
XS GIS Cut Line= 6
922729.442771957804087.315704191922622.839713422804064.036581581
922501.523189627804061.943615307922455.433873299804057.367490232
922403.945182168804044.843997712922358.879099458804027.460641087
#Sta/Elev= 30
9810.83798.880289819.88199.286739825.77899.371329836.12397.973989846.46897.54131
9867.15897.918359877.39498.505069887.521 98.84259917.90198.137499927.944 98.3386
9947.98498.035469968.02498.074839978.02798.483139988.02896.68982 9998.0388.58958
10008.0393.1919810018.0396.7464710028.0397.7802710038.0398.2113210068.1697.51051
10088.2797.9928210098.5797.4712610119.1597.7587510129.44 97.643310139.7398.14916
 10150.499.6525310161.12100.808310171.84 101.80210182.56106.847410189.12110.4637
#Mann= 3 , 0 , 0
9810.837    0.04       09810.837    0.04       010189.12    0.04       0
#XS Ineff= 2 , 0
       09964.222        10048.26       0
Bank Sta=9810.837,10189.12
Exp/Cntr=0.3,0.1

Type RM Length L Ch R = 1 ,11528.86,208.466600,208.466600,208.466600
XS GIS Cut Line= 6
 922749.00560678803919.366903194922714.801325432803904.431725635
922669.098850636803887.385807475922477.432448342803828.472358517
922425.841389496 803810.23239083922385.855170562803794.185646166
#Sta/Elev= 30
9807.79294.605799812.16394.578159823.07593.912059844.89893.448569866.24993.49679
9876.92293.787339898.18192.62185 9902.0192.572599919.10692.451349950.49293.23052
9960.95493.163839971.41693.542039981.87893.075999992.34190.29657 10002.884.47301
10004.1485.1796410013.2690.7308110023.7295.1203510034.1895.8760410044.64   96.42
10055.1197.45324 10072.297.7940510076.03 97.987910086.49 98.802810096.99 100.247
 10107.699.85927 10118.2100.171510128.81100.175110149.13100.444210192.22102.3402
#Mann= 3 , 0 , 0
9807.792  0.0417       09807.792  0.0417       010192.22  0.0417       0
#XS Ineff= 2 , 0
       09965.858                       0
Bank Sta=9807.792,10192.22
Exp/Cntr=0.3,0.1

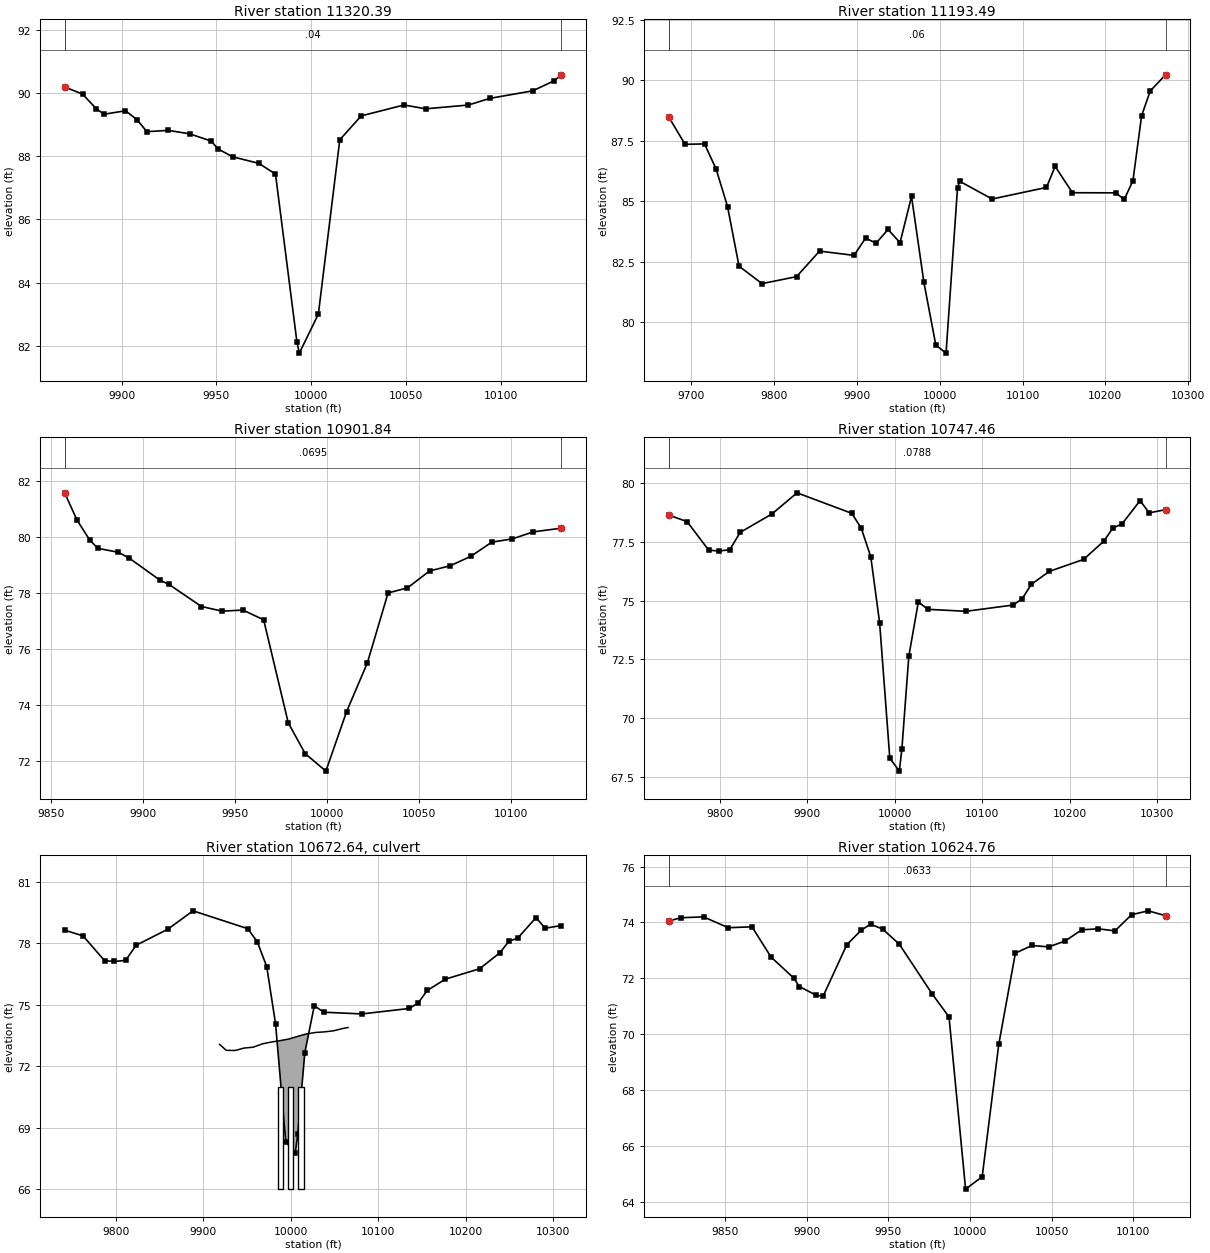
Type RM Length L Ch R = 1 ,11320.39,126.897300,126.897300,126.897300
XS GIS Cut Line= 2
922773.369257645803732.823965784922541.598424312803610.428132451
#Sta/Elev= 26
9869.985 90.19639879.44989.968689886.73989.504319890.758 89.33179902.067 89.4428
9908.15489.161759913.37588.779769924.68488.821469935.993 88.71129947.30288.48269
9950.98388.23116 9958.6187.983989972.39787.777699981.22887.437689992.53782.11864
9993.81181.7658610003.8583.0028710015.1588.5245610026.4689.2805410049.08  89.626
10060.3989.5040410083.0189.6241410094.32 89.835310116.9390.0739110128.2490.39231
10132.0990.58083
#Mann= 3 , 0 , 0
9869.985    0.04       09869.985    0.04       010132.09    0.04       0
#XS Ineff= 2 , 0
       09947.423                       0
Bank Sta=9869.985,10132.09
Exp/Cntr=0.3,0.1

Type RM Length L Ch R = 1 ,11193.49,291.652500,291.652500,291.652500
XS GIS Cut Line= 3
922968.681757645803816.157299117922697.848424312803534.907299117
922497.327590979803475.011465784
#Sta/Elev= 30
9672.85588.492999692.57987.35639 9716.1187.373599729.99286.344519743.87584.78266
9757.758 82.31359785.52381.591159827.17181.879189854.93782.937359896.58582.75991
9910.46883.471929923.24683.266789937.66383.832189952.11683.286159965.99985.19858
9980.91381.643649995.32979.0452310007.65 78.714410021.5385.5664310024.16 85.8261
10063.3185.09256 10128.985.5730310139.34 86.443710160.2185.3540410212.3985.34784
10222.8385.0788210233.2685.85133 10243.788.5357710254.1489.5648910272.5890.23282
#Mann= 3 , 0 , 0
9672.855    0.06       09672.855    0.06       010272.58    0.06       0
#XS Ineff= 2 , 0
       09964.101                       0
Bank Sta=9672.855,10272.58
Exp/Cntr=0.3,0.1

Type RM Length L Ch R = 1 ,10901.84,154.376100,154.376100,154.376100
XS GIS Cut Line= 2
923150.973424312803631.261465784922911.390090979803506.261465784
#Sta/Elev= 26
9857.37281.58415 9864.1180.611839870.90979.911789875.38979.605159886.66879.46126
9892.52779.253099909.22778.467569914.14678.315979931.78577.528459943.06577.36253
9954.34477.401519965.62377.055129979.001 73.37819988.18272.283099999.46171.65546
10010.7473.7808110022.0275.51561 10033.378.0131110043.8678.1931110055.8678.79602
10067.1478.9829110078.4279.3228710089.6979.8243910100.9779.9423810112.2580.19182
 10127.680.32307
#Mann= 3 , 0 , 0
9857.372  0.0695       09857.372  0.0695       0 10127.6  0.0695       0
#XS Ineff= 2 , 0
       0                               0
Bank Sta=9857.372,10127.6
Exp/Cntr=0.3,0.1

Type RM Length L Ch R = 1 ,10747.46,122.702400,122.702400,122.702400
XS GIS Cut Line= 4
923236.743990551803592.891740891923143.519831897 803453.96946525
922942.448117154803368.057005314922766.967347923803320.530963647
#Sta/Elev= 30
9741.61378.62914 9762.6978.349839787.24677.141739798.58277.102419811.33277.15596
9823.37577.895349859.50378.674329888.31379.572669950.80578.703179961.67978.07318
9972.55476.855279982.64774.065339994.30368.3111910005.1867.76038 10008.168.70308
10016.0572.6448510026.9374.94258 10037.874.62811 10081.3 74.544610135.2974.80982
10145.6575.0801510156.0175.6892610176.7376.2403110215.7776.7460910238.8977.52212
10249.2578.0805310259.6178.2500610280.3379.2422410290.6978.7228210309.3878.85689
#Mann= 3 , 0 , 0
9741.613  0.0788       09741.613  0.0788       010309.38  0.0788       0
#XS Ineff= 2 , 0
       0                               0
Bank Sta=9741.613,10309.38
Exp/Cntr=0.3,0.1

Type RM Length L Ch R = 2 ,10672.64,,,
Bridge Culvert--1,0,-1,-1, 0
Deck Dist Width WeirC Skew NumUp NumDn MinLoCord MaxHiCord MaxSubmerge Is_Ogee
43.851,35,2.6,0,19,19, , , 0.95, 0, 0,0,,
 9918.74 9926.26 9936.47 9946.68 9956.90 9965.43 9967.11 9977.33 9987.54 9997.75
10007.9710014.5610018.1810028.3910038.6110048.8210059.0410063.7010065.48
   73.06   72.77   72.76   72.88   72.92   73.05   73.08   73.17   73.24   73.32
   73.45   73.53   73.57   73.64   73.67   73.72   73.83   73.87   73.88
                                                                                
                                                                        
 9918.74 9926.26 9936.47 9946.68 9956.90 9965.43 9967.11 9977.33 9987.54 9997.75
10007.9710014.5610018.1810028.3910038.6110048.8210059.0410063.7010065.48
   73.06   72.77   72.76   72.88   72.92   73.05   73.08   73.17   73.24   73.32
   73.45   73.53   73.57   73.64   73.67   73.72   73.83   73.87   73.88
                                                                                
                                                                        
BR Coef=-1 , 0 , 0 ,, 0 ,,,0.8,-1,,0,
WSPro=,,,, 1 ,,,, 0 ,,,, 0 ,,,,-1 ,-1 ,-1 , 0 , 0 , 0 , 0 , 0
Multiple Barrel Culv=2,5,5.91,35,0.013,0.7,1,8,3,66,64,3,Culvert #1, 0, 43.851
 9988.18 9988.1810000.0010000.0010011.8210011.82
Culvert Bottom n=0.013
BC Design=,, 0 ,, 0 ,,,,,,

Type RM Length L Ch R = 1 ,10624.76,89.402300,89.402300,89.402300
XS GIS Cut Line= 3
923260.507011385803410.099272942923166.765358073803321.131925186
922994.523103799803289.815151682
#Sta/Elev= 30
9815.39474.052049822.80274.169569836.77374.200519851.85573.812739866.38173.84493
9878.13372.75982 9891.9272.013989895.43471.708269905.70771.394949909.96171.35835
9924.48873.20275 9933.28 73.72239939.01473.939579946.42773.763019956.59173.22779
9976.91971.430399987.083 70.62149997.24764.4555310007.4164.8992910017.57 69.6393
10027.74 72.9023 10037.973.1765510048.0773.1256610058.2373.3367810068.3973.73726
10078.5673.7730510088.7273.6991410098.8974.2769310109.0574.41717 10119.774.24477
#Mann= 3 , 0 , 0
9815.394  0.0633       09815.394  0.0633       0 10119.7  0.0633       0
#XS Ineff= 2 , 0
       0                               0
Bank Sta=9815.394,10119.7
Exp/Cntr=0.3,0.1

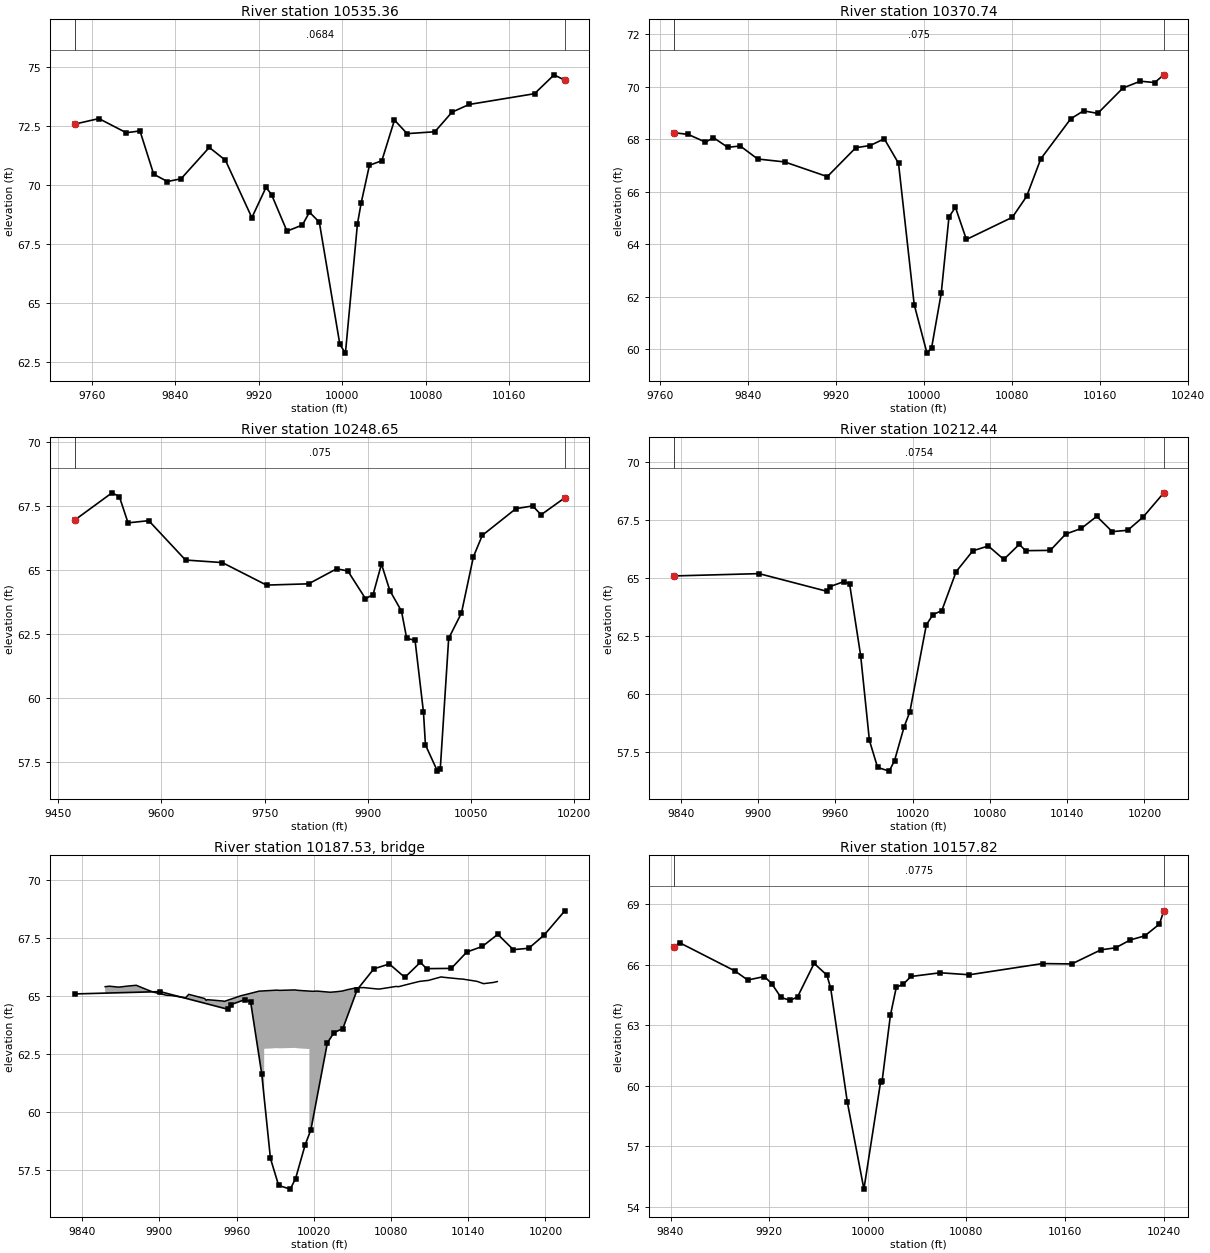
Type RM Length L Ch R = 1 ,10535.36,164.618200,164.618200,164.618200
XS GIS Cut Line= 6
923309.860977731803402.787574224923234.830393599803314.570596305
923154.409471913803240.368750212923101.504996946803209.076964629
923070.059274119803187.601945784  922957.1278523803096.313693909
#Sta/Elev= 30
9743.33372.595119766.68572.83062 9792.9472.230949806.06872.307819819.19670.47432
9832.32370.163529845.45170.279599872.51871.608749888.00371.064899913.33768.63221
9926.94469.918359932.24369.60583 9946.9968.061719961.73668.318339968.56668.86425
9978.01768.440739997.72463.2579910003.0562.8913510014.56  68.36310018.1369.25227
10026.0770.8523510037.9771.0456110050.0872.7677110062.1972.1923210088.82 72.2731
10105.2173.10163 10121.673.4287510184.3573.8852410203.1474.6851710213.4174.45618
#Mann= 3 , 0 , 0
9743.333  0.0684       09743.333  0.0684       010213.41  0.0684       0
#XS Ineff= 2 , 0
       0                               0
Bank Sta=9743.333,10213.41
Exp/Cntr=0.3,0.1

Type RM Length L Ch R = 1 ,10370.74,122.096000,122.096000,122.096000
XS GIS Cut Line= 2
923453.090144398803323.368837579923108.605635851 803041.51787604
#Sta/Elev= 30
9772.653 68.25469785.86968.188819801.66167.893949808.947  68.0629821.86767.69605
9833.24467.745329849.036 67.2495 9873.5567.137559912.31266.577179938.15367.68104
9951.07467.762349963.99468.019029976.91567.087259991.16361.6941910002.7659.84313
10006.9560.0436910015.6862.1227310022.7565.04386 10028.665.4046210038.5464.17879
10080.2865.02589 10093.265.8208710106.1267.2572910133.2968.7832410144.8869.08632
 10157.868.9900110180.6769.9572210196.4670.2170810209.4970.1658910217.7570.46058
#Mann= 3 , 0 , 0
9772.653   0.075       09772.653   0.075       010217.75   0.075       0
#XS Ineff= 2 , 0
       09866.437                       0
Bank Sta=9772.653,10217.75
Exp/Cntr=0.3,0.1

Type RM Length L Ch R = 1 ,10248.65,36.209000,36.209000,36.209000
XS GIS Cut Line= 4
923622.436097923803475.904561403923546.222291289803273.854597166
923438.310461909803149.047505221923166.765358073802958.752117493
#Sta/Elev= 30
9473.72966.947329528.13568.015269538.82367.868649551.46766.843289581.57466.92836
9635.01265.392049688.45165.292669752.70264.414349813.85964.463349854.66665.05059
9870.91964.965019896.56863.884739907.55264.039619919.76365.236249931.97464.19956
9948.84263.399229956.39762.342759968.608 62.25319980.81959.457799983.69258.17593
10001.1257.1532810005.2457.2354110017.4562.3335610035.97  63.32110053.3965.51921
 10066.366.3546910115.1467.3967410139.5667.5042710151.7767.1579410186.2567.82286
#Mann= 3 , 0 , 0
9473.729   0.075       09473.729   0.075       010186.25   0.075       0
#XS Ineff= 2 , 0
       09864.103                       0
Bank Sta=9473.729,10186.25
Exp/Cntr=0.3,0.1

Type RM Length L Ch R = 1 ,10212.44,54.615000,54.615000,54.615000
XS GIS Cut Line= 3
923465.541936308 803143.83164677923329.333291709803027.477143541
923161.727400094802915.278158262
#Sta/Elev= 30
9834.18965.106039900.661 65.20619953.26864.445059955.55864.64366 9966.4264.85952
9970.95464.764699979.57261.66435 9986.3558.014249992.72456.8485310001.7556.68852
10005.8857.1447210013.3358.6016510017.7859.2484810030.5862.9983710035.7663.43822
10042.6163.6129110053.7365.2905510066.6866.1898910078.7166.3989710090.7565.81961
10102.7866.4691810107.6666.1967210126.8566.2087810138.8866.9145110150.9267.15376
10162.95 67.677610174.98 67.016810187.0267.0762810199.0567.6508610215.0268.69096
#Mann= 3 , 0 , 0
9834.189  0.0754       09834.189  0.0754       010215.02  0.0754       0
#XS Ineff= 2 , 0
       09881.345                       0
Bank Sta=9834.189,10215.02
Exp/Cntr=0.3,0.1

Type RM Length L Ch R = 3 ,10187.53,,,
BEGIN DESCRIPTION:
END DESCRIPTION:
Bridge Culvert--1,0,-1,-1, 0
Deck Dist Width WeirC Skew NumUp NumDn MinLoCord MaxHiCord MaxSubmerge Is_Ogee
15.002500,24.610000,2.6,0, 51, 51, , , 0.95, 0, 0,0,,
 9857.97 9861.36 9868.52 9876.12 9882.11 9890.88 9895.71 9905.64 9909.31 9920.40
 9922.90 9935.16 9936.50 9937.23 9949.74 9950.25 9964.01 9964.30 9977.77 9978.86
 9981.50 9981.50 9991.53 9993.4210005.2910007.9810016.6010016.6010019.0410022.54
10032.8010037.1010041.9110046.1610052.9410058.7410069.4310071.3210083.9010085.91
10096.4810102.3910109.0610118.8710121.6410134.2210135.3610146.8010151.8410159.38
10162.56
   65.42   65.44   65.40   65.45   65.48   65.28   65.18   65.05   65.04   64.94
   65.09   64.91   64.83   64.86   64.80   64.78   65.04   65.04   65.23   65.23
   65.24   65.24   65.27   65.26   65.28   65.26   65.23   65.23   65.22   65.23
   65.18   65.20   65.23   65.29   65.37   65.38   65.32   65.32   65.43   65.42
   65.57   65.65   65.69   65.84   65.82   65.75   65.75   65.65   65.55   65.60
   65.64
 -934.58 -934.56 -934.60 -934.55 -934.52 -934.72 -934.82 -934.95 -934.96 -935.06
 -934.91 -935.09 -935.17 -935.14 -935.20 -935.22 -934.96 -934.96 -934.77 -934.77
 -934.76   62.74   62.77   62.76   62.78   62.76   62.73 -934.77 -934.78 -934.77
 -934.82 -934.80 -934.77 -934.71 -934.63 -934.62 -934.68 -934.68 -934.57 -934.58
 -934.43 -934.35 -934.31 -934.16 -934.18 -934.25 -934.25 -934.35 -934.45 -934.40
 -934.36
 9857.97 9861.36 9868.52 9876.12 9882.11 9890.88 9895.71 9905.64 9909.31 9920.40
 9922.90 9935.16 9936.50 9937.23 9949.74 9950.25 9964.01 9964.30 9976.61 9976.61
 9977.77 9978.86 9991.53 9993.4210005.2910007.9810011.7110011.7110019.0410022.54
10032.8010037.1010041.9110046.1610052.9410058.7410069.4310071.3210083.9010085.91
10096.4810102.3910109.0610118.8710121.6410134.2210135.3610146.8010151.8410159.38
10162.56
   65.42   65.44   65.40   65.45   65.48   65.28   65.18   65.05   65.04   64.94
   65.09   64.91   64.83   64.86   64.80   64.78   65.04   65.04   65.22   65.22
   65.23   65.23   65.27   65.26   65.28   65.26   65.25   65.25   65.22   65.23
   65.18   65.20   65.23   65.29   65.37   65.38   65.32   65.32   65.43   65.42
   65.57   65.65   65.69   65.84   65.82   65.75   65.75   65.65   65.55   65.60
   65.64
 -934.58 -934.56 -934.60 -934.55 -934.52 -934.72 -934.82 -934.95 -934.96 -935.06
 -934.91 -935.09 -935.17 -935.14 -935.20 -935.22 -934.96 -934.96 -934.78   62.72
   62.73   62.73   62.77   62.76   62.78   62.76   62.75 -934.75 -934.78 -934.77
 -934.82 -934.80 -934.77 -934.71 -934.63 -934.62 -934.68 -934.68 -934.57 -934.58
 -934.43 -934.35 -934.31 -934.16 -934.18 -934.25 -934.25 -934.35 -934.45 -934.40
 -934.36
BR Coef=-1 , 0 , 0 ,, 0 ,,,0.8,0,1,0,
WSPro=,,,, 1 ,,,, 0 ,,,, 0 ,,,,-1 ,-1 ,-1 , 0 , 0 , 0 , 0 , 0
BC Design=,, 0 ,, 0 ,,,,,,

Type RM Length L Ch R = 1 ,10157.82,45.181000,45.181000,45.181000
XS GIS Cut Line= 3
923499.709528536803108.278881893923369.041574508802990.539206013
 923182.04326576802871.414357454
#Sta/Elev= 30
9842.44466.850249847.34267.079559892.158 65.68389902.62665.231949916.08765.40479
9922.03665.059199929.54764.373879936.97464.225429943.00864.394779956.46966.05449
9966.85265.473539969.92964.81882 9983.3959.199089996.85154.8874110010.3160.16374
10011.67 60.260510018.3363.4844810023.1264.8745810028.6465.0203810034.9865.40714
10058.6965.5911310082.4165.4924310141.6966.04603 10165.466.0278310189.1266.72722
10200.9766.8261810212.83 67.213810224.69  67.41910236.5468.0000910240.0568.65569
#Mann= 3 , 0 , 0
9842.444  0.0775       09842.444  0.0775       010240.05  0.0775       0
#XS Ineff= 2 , 0
       09939.466                       0
Bank Sta=9842.444,10240.05
Exp/Cntr=0.3,0.1