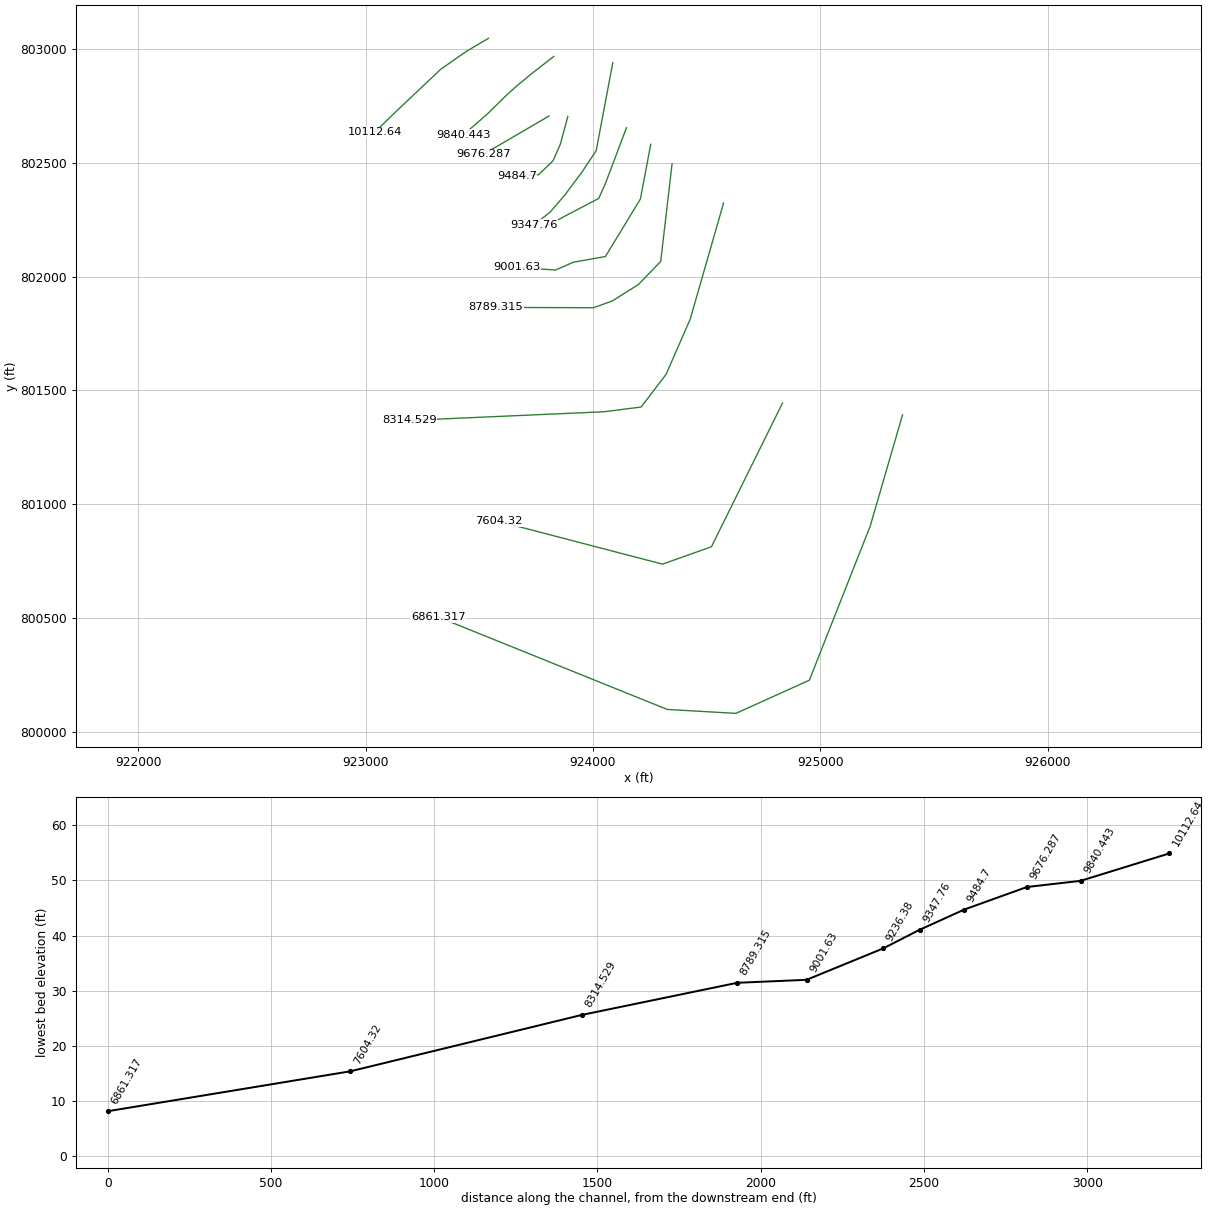
HEC-RAS study 13263_ras.prj: 13263

--- 13263_ras.g01 (geometry) --- (continued)

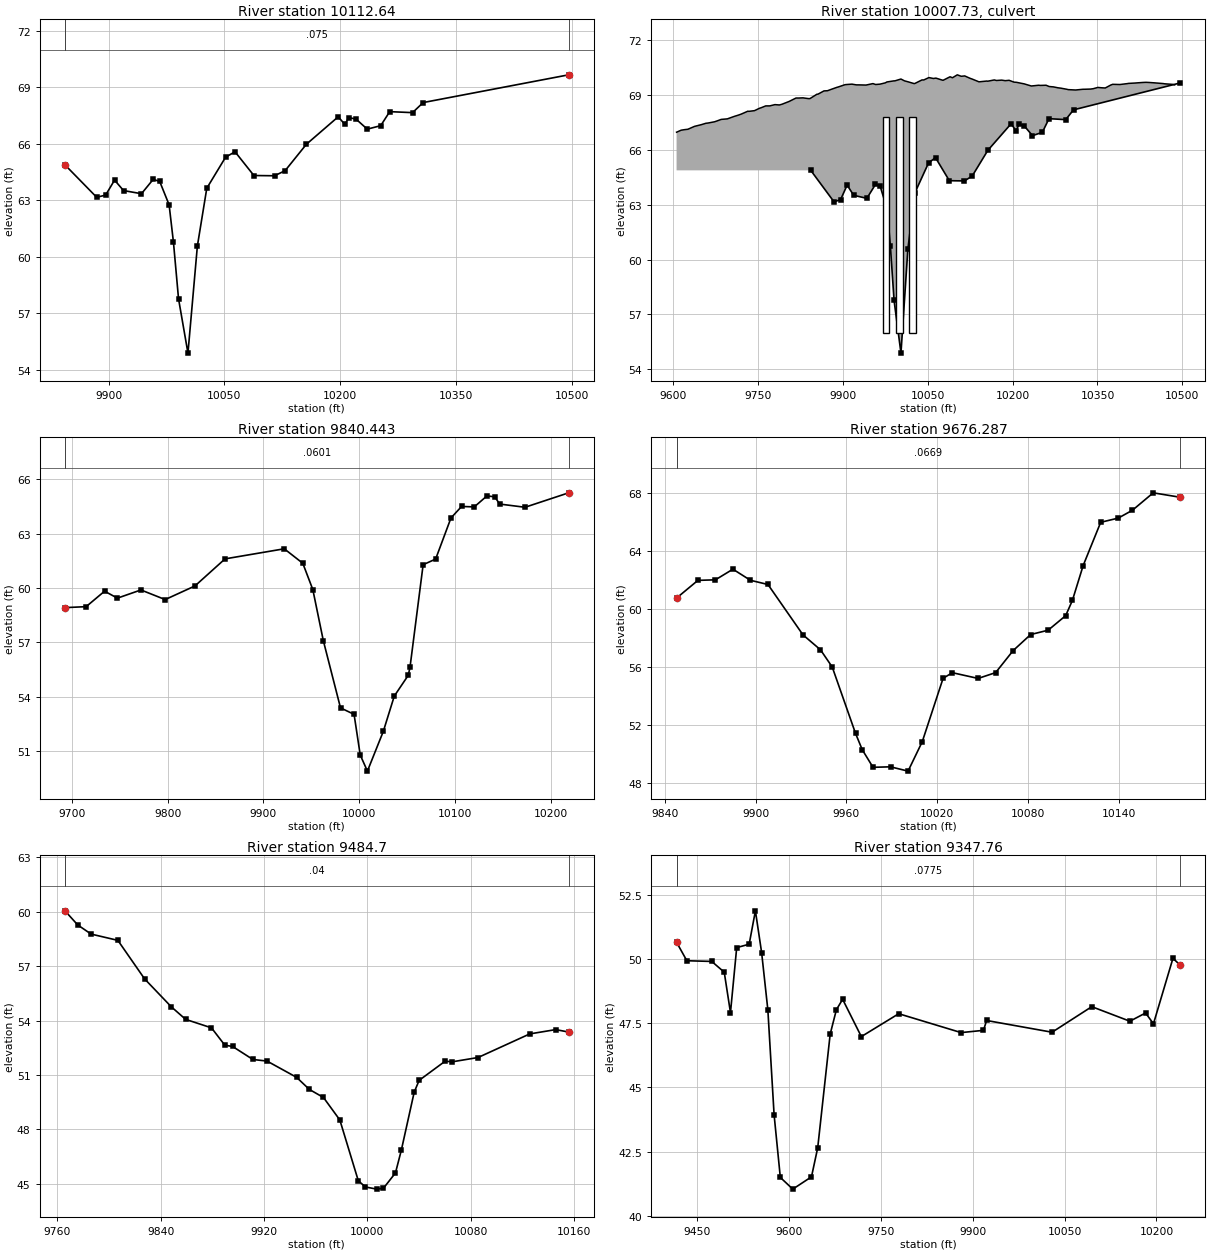
Type RM Length L Ch R = 1 ,10112.64,272.197000,272.197000,272.197000
XS GIS Cut Line= 5
923540.329727731 803048.22861322923441.905582432802990.068890998
923330.059962774802911.776957237923126.500934996802719.402491425
923039.261351663802634.399820485
#Sta/Elev= 30
9843.445 64.88149884.48263.161039896.09763.273469907.71264.071859919.32863.51662
9942.55963.348529957.768 64.11069966.19864.002299978.40462.758799984.04560.76557
9990.61157.7663210002.8254.8776810015.0260.5657310027.2363.6386110051.6465.29273
10063.8565.5766510088.2664.3159110115.0164.3021510128.7764.5743210156.2965.97578
10197.5767.4379810206.0767.0332210211.3367.3929510220.6367.3142910235.1966.78026
10252.6166.9640110264.3167.7099610293.8867.6573310307.6468.1926410496.1869.66644
#Mann= 3 , 0 , 0
9843.445   0.075       09843.445   0.075       010496.18   0.075       0
#XS Ineff= 2 , 0
       09959.595                       0
Bank Sta=9843.445,10496.18
Exp/Cntr=0.3,0.1

Type RM Length L Ch R = 2 ,10007.73,,,
Bridge Culvert--1,0,-1,-1, 0
Deck Dist Width WeirC Skew NumUp NumDn MinLoCord MaxHiCord MaxSubmerge Is_Ogee
54.599,163,2.6,0,127,127, , , 0.95, 0, 0,0,,
 9606.40 9614.53 9620.53 9626.31 9638.10 9639.44 9649.88 9658.35 9661.66 9673.44
 9677.26 9685.23 9696.17 9697.01 9708.79 9715.08 9720.57 9732.36 9733.99 9744.14
 9752.90 9755.92 9763.93 9767.89 9771.02 9780.25 9788.02 9792.61 9804.98 9805.03
 9817.34 9822.04 9829.70 9839.05 9842.06 9854.43 9856.05 9866.79 9873.06 9879.15
 9890.07 9891.52 9903.88 9907.08 9916.24 9924.08 9928.60 9940.97 9941.09 9953.33
 9958.10 9965.69 9975.11 9978.05 9990.42 9992.1110002.7810009.1210015.1410026.13
10027.5110039.8710043.1410052.2310060.1510064.5910076.9610077.1510089.3210089.88
10093.7910102.3510109.3210115.4210124.8610128.4910140.3910141.5610154.6310155.93
10167.6910171.4610180.7610187.0010193.8310202.5310206.9010218.0710219.9610233.03
10233.6010246.1010249.1310259.1710264.6710272.2310280.2010285.3010295.7410298.37
10311.2710311.4410324.5010326.8110337.5710342.3410350.6410357.8810363.7110373.41
10376.7710388.9410389.8410402.9110404.4810415.9810420.0110429.0410435.5510442.11
10451.0810455.1810466.6210468.2510481.3210482.1510486.33
   66.97   67.08   67.11   67.13   67.29   67.30   67.38   67.46   67.47   67.54
   67.58   67.67   67.70   67.71   67.84   67.90   67.96   68.12   68.11   68.15
   68.28   68.31   68.41   68.41   68.41   68.48   68.46   68.50   68.65   68.65
   68.84   68.84   68.85   68.81   68.81   69.05   69.05   69.23   69.24   69.31
   69.43   69.44   69.57   69.58   69.60   69.56   69.56   69.55   69.55   69.63
   69.58   69.60   69.67   69.72   69.78   69.78   69.88   69.78   69.73   69.63
   69.64   69.83   69.83   69.96   69.91   69.93   69.81   69.81   70.00   70.00
   69.95   70.11   70.03   70.05   69.92   69.88   69.73   69.73   69.77   69.76
   69.83   69.80   69.82   69.79   69.81   69.71   69.70   69.63   69.62   69.50
   69.50   69.54   69.53   69.54   69.47   69.45   69.40   69.38   69.32   69.30
   69.28   69.28   69.32   69.32   69.33   69.35   69.42   69.40   69.39   69.55
   69.59   69.58   69.58   69.63   69.64   69.66   69.67   69.69   69.70   69.69
   69.67   69.66   69.63   69.62   69.59   69.59   69.56
                                                                                
                                                                                
                                                                                
                                                                                
                                                                                
                                                                                
                                                                                
                                                                                
                                                                                
                                                                                
                                                                                
                                                                                
                                                        
 9606.40 9614.53 9620.53 9626.31 9638.10 9639.44 9649.88 9658.35 9661.66 9673.44
 9677.26 9685.23 9696.17 9697.01 9708.79 9715.08 9720.57 9732.36 9733.99 9744.14
 9752.90 9755.92 9763.93 9767.89 9771.02 9780.25 9788.02 9792.61 9804.98 9805.03
 9817.34 9822.04 9829.70 9839.05 9842.06 9854.43 9856.05 9866.79 9873.06 9879.15
 9890.07 9891.52 9903.88 9907.08 9916.24 9924.08 9928.60 9940.97 9941.09 9953.33
 9958.10 9965.69 9975.11 9978.05 9990.42 9992.1110002.7810009.1210015.1410026.13
10027.5110039.8710043.1410052.2310060.1510064.5910076.9610077.1510089.3210089.88
10093.7910102.3510109.3210115.4210124.8610128.4910140.3910141.5610154.6310155.93
10167.6910171.4610180.7610187.0010193.8310202.5310206.9010218.0710219.9610233.03
10233.6010246.1010249.1310259.1710264.6710272.2310280.2010285.3010295.7410298.37
10311.2710311.4410324.5010326.8110337.5710342.3410350.6410357.8810363.7110373.41
10376.7710388.9410389.8410402.9110404.4810415.9810420.0110429.0410435.5510442.11
10451.0810455.1810466.6210468.2510481.3210482.1510486.33
   66.97   67.08   67.11   67.13   67.29   67.30   67.38   67.46   67.47   67.54
   67.58   67.67   67.70   67.71   67.84   67.90   67.96   68.12   68.11   68.15
   68.28   68.31   68.41   68.41   68.41   68.48   68.46   68.50   68.65   68.65
   68.84   68.84   68.85   68.81   68.81   69.05   69.05   69.23   69.24   69.31
   69.43   69.44   69.57   69.58   69.60   69.56   69.56   69.55   69.55   69.63
   69.58   69.60   69.67   69.72   69.78   69.78   69.88   69.78   69.73   69.63
   69.64   69.83   69.83   69.96   69.91   69.93   69.81   69.81   70.00   70.00
   69.95   70.11   70.03   70.05   69.92   69.88   69.73   69.73   69.77   69.76
   69.83   69.80   69.82   69.79   69.81   69.71   69.70   69.63   69.62   69.50
   69.50   69.54   69.53   69.54   69.47   69.45   69.40   69.38   69.32   69.30
   69.28   69.28   69.32   69.32   69.33   69.35   69.42   69.40   69.39   69.55
   69.59   69.58   69.58   69.63   69.64   69.66   69.67   69.69   69.70   69.69
   69.67   69.66   69.63   69.62   69.59   69.59   69.56
                                                                                
                                                                                
                                                                                
                                                                                
                                                                                
                                                                                
                                                                                
                                                                                
                                                                                
                                                                                
                                                                                
                                                                                
                                                        
BR Coef=-1 , 0 , 0 ,, 0 ,,,0.8,-1,,0,
WSPro=,,,, 1 ,,,, 0 ,,,, 0 ,,,,-1 ,-1 ,-1 , 0 , 0 , 0 , 0 , 0
Multiple Barrel Culv=2,11.81,11.81,163,0.013,0.7,1,8,3,56,52,3,Culvert #1, 0, 54.599
 9976.38 9976.3810000.0010000.0010023.6210023.62
Culvert Bottom n=0.013
BC Design=,, 0 ,, 0 ,,,,,,

Type RM Length L Ch R = 1 ,9840.443,164.155800,164.155800,164.155800
XS GIS Cut Line= 6
923827.673165568802968.546867571923731.682906985802894.111281311
923662.359813007802836.749449533 923619.12702171802797.676911146
923535.458143316802715.492462002923430.595360868802624.454826443
#Sta/Elev= 30
9692.71458.92402 9714.8258.977229734.05959.831319747.45859.447269772.02259.89945
9797.33159.368249828.47560.121359859.847  61.6149921.68462.170039941.03961.37054
9951.51259.917399962.43457.10764  9980.453.393239994.57353.03536   1000150.79276
 10008.549.9027910025.1252.0994310036.5854.0459210051.1755.19134   10053 55.6435
10066.6861.2919810079.7461.6034410095.7563.8719410106.8464.5065210120.08 64.4814
10133.3265.0888210141.51 65.036910146.5664.6385910173.0564.4612110218.6165.25806
#Mann= 3 , 0 , 0
9692.714  0.0601       09692.714  0.0601       010218.61  0.0601       0
#XS Ineff= 2 , 0
       0                               0
Bank Sta=9692.714,10218.61
Exp/Cntr=0.3,0.1

Type RM Length L Ch R = 1 ,9676.287,191.587000,191.587000,191.587000
XS GIS Cut Line= 2
923807.184222484802706.853928966923519.577326465802539.083239622
#Sta/Elev= 30
9847.78160.733169861.88661.953839873.46361.99237 9885.0462.725339896.617 61.9593
9908.19561.669429931.34958.193129942.92657.161759950.69255.97296 9966.0851.39491
9970.53850.265149977.65749.051959989.23449.0861210000.8148.7884210010.2350.82829
10023.9655.1911910030.0855.5830210047.12 55.1858 10058.755.5869410070.2757.10641
10081.8558.2151710093.4358.51504   1010559.5182610109.4660.5731410116.5862.97955
10128.1665.9619710139.74 66.250710149.1666.7952110162.8967.9961310180.7467.69018
#Mann= 3 , 0 , 0
9847.781  0.0669       09847.781  0.0669       010180.74  0.0669       0
#XS Ineff= 2 , 0
       0                10163.31       0
Bank Sta=9847.781,10180.74
Exp/Cntr=0.3,0.1

Type RM Length L Ch R = 1 ,  9484.7,136.939900,136.939900,136.939900
XS GIS Cut Line= 6
923889.365087777802704.530379981923856.506040931802582.843878493
923824.476567745802510.188289106 923803.34745577802489.361119643
923760.393982112802448.454046711923664.972726673802442.377602205
#Sta/Elev= 30
9765.88260.042829775.75359.265269786.11258.761439806.82858.415859827.54456.29317
9848.26154.751949859.34454.061599879.33553.595159889.69352.63849 9895.6652.57079
9911.42751.851819922.35651.765119945.24150.869279955.14250.20197 9966.07 49.7585
9978.74748.518519993.045 45.17049998.57944.8282710007.3244.7095210012.5344.76007
10021.8245.6029610026.3446.8483910036.3250.0509110040.15 50.702410060.3251.76056
10065.7251.7234410085.7651.9604810125.8453.2620310145.8853.4980910155.9353.36488
#Mann= 3 , 0 , 0
9765.882    0.04       09765.882    0.04       010155.93    0.04       0
#XS Ineff= 2 , 0
       0                10101.52       0
Bank Sta=9765.882,10155.93
Exp/Cntr=0.3,0.1

Type RM Length L Ch R = 1 , 9347.76,111.380500,111.380500,111.380500
XS GIS Cut Line= 6
924087.281754494802941.509546652924014.117495209802554.532032251
923951.959862083802460.686194032923875.570973188802358.255638465
923812.003773868802284.717113718923740.927587807 802227.53385222
#Sta/Elev= 30
9416.292 50.64549433.09549.927439473.80349.900189494.15749.481429504.335 47.9085
9514.51250.439129534.86650.570269545.04351.87021 9555.2250.244379565.39848.01173
9575.57543.934649585.75241.492079606.10641.036779636.63841.515689646.81542.64608
9667.16947.069359677.346  48.0229687.52448.426229718.05546.974049779.11847.86465
9880.96547.130219917.51547.21723 9922.6947.6011610029.5847.1444210094.4348.13927
10156.6647.5730810182.3347.8935310195.1747.4723710226.9950.02196 10238.949.75478
#Mann= 3 , 0 , 0
9416.292  0.0775       09416.292  0.0775       0 10238.9  0.0775       0
#XS Ineff= 2 , 0
       09883.297        10070.06       0
Bank Sta=9416.292,10238.9
Exp/Cntr=0.3,0.1

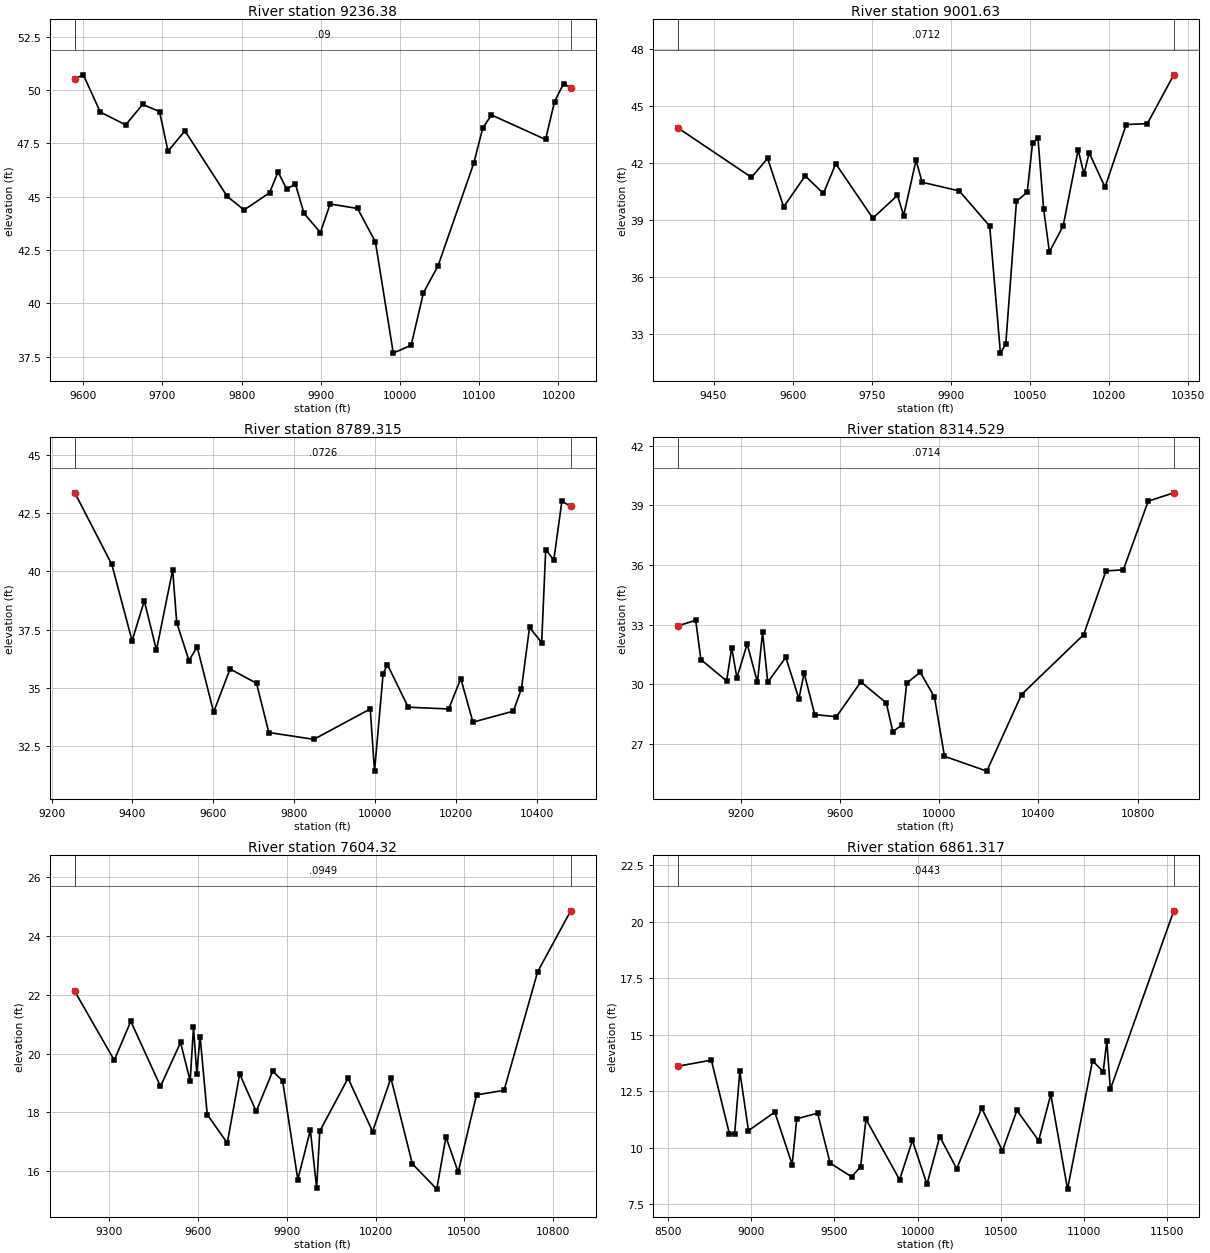
Type RM Length L Ch R = 1 , 9236.38,234.750100,234.750100,234.750100
XS GIS Cut Line= 5
924147.177587807802655.051213324924055.504855007802411.671992049
924025.034303159802344.125796139923879.215151906802267.744335935
923766.969254494802208.002602205
#Sta/Elev= 30
9589.52250.519919600.26350.705949621.63548.961629653.692 48.36079675.06449.31637
9696.43648.984579707.12247.129939728.49348.079769781.92345.004519803.295 44.3745
9835.35245.181669846.03846.155959856.91445.349669867.88445.588659878.85544.20991
 9899.4643.317289911.76644.652549946.31244.443829968.88942.880699991.46737.66486
10014.0438.0372310029.5740.4965510047.9141.7498910093.0846.5675910104.4148.21331
10115.4348.8255710183.71 47.675510195.0449.4529410206.3650.2891810215.4650.09134
#Mann= 3 , 0 , 0
9589.522    0.09       09589.522    0.09       010215.46    0.09       0
#XS Ineff= 2 , 0
       09931.284        10091.97       0
Bank Sta=9589.522,10215.46
Exp/Cntr=0.3,0.1

Type RM Length L Ch R = 1 , 9001.63,212.314700,212.314700,212.314700
XS GIS Cut Line= 6
 924253.94842115802582.134546652924208.510741115802341.677167371
924054.704112768802088.750711918923914.307258457802063.895346671
923835.447617382  802029.4636724923664.972726673802040.901907772
#Sta/Elev= 30
9382.42643.836429521.98741.230379552.51842.232299583.04939.675799623.75741.30903
9658.36140.381119681.76941.946429751.99239.081949798.80740.281719810.51139.21957
9833.91842.127019845.62240.972129915.84540.516999973.63638.663499993.94731.97144
 10004.132.4577610024.4139.9744610044.7240.4456410054.8843.0351810065.0443.32186
10075.8939.5684210086.8137.3036210112.9638.6754910141.3642.6842510152.2441.40411
10162.2642.5187910192.3340.7130910232.4244.0142410272.5144.0604210322.6546.63214
#Mann= 3 , 0 , 0
9382.426  0.0712       09382.426  0.0712       010322.65  0.0712       0
#XS Ineff= 2 , 0
       09905.059        10057.07       0
Bank Sta=9382.426,10322.65
Exp/Cntr=0.3,0.1

Type RM Length L Ch R = 1 ,8789.315,474.785600,474.785600,474.785600
XS GIS Cut Line= 6
 924347.69842115802496.197046652924297.733240038802067.025354668
924199.137987614801965.300094262924084.892695159801893.309909955
924001.947482795801863.574833855923573.136385053801865.139837846
#Sta/Elev= 30
9257.54343.365649349.01240.293349399.16137.020679429.25138.73552 9459.3436.62016
 9499.4640.064639509.489 37.79889539.72136.173569560.054 36.75579600.72133.96223
9641.38835.813679706.90935.197219737.19433.088279848.53832.795639987.99534.09797
9998.61831.4327910019.8635.6102510030.4936.0001110081.9234.1738810181.9334.09808
10211.9335.4019910241.9333.5332910341.9334.0043710361.9334.9660510381.9337.59465
10411.9336.9439310421.9340.9347310441.9340.4840210461.9343.0097910483.7942.78566
#Mann= 3 , 0 , 0
9257.543  0.0726       09257.543  0.0726       010483.79  0.0726       0
#XS Ineff= 2 , 0
       09884.509        10153.12       0
Bank Sta=9257.543,10483.79
Exp/Cntr=0.3,0.1

Type RM Length L Ch R = 1 ,8314.529,710.209400,710.209400,710.209400
XS GIS Cut Line= 6
924574.260921121802324.322046667924427.593246728801813.443770424
924321.245860219801570.364029899924211.870860219801427.134863228
924050.412526906801406.301529899923191.882448912 801368.15885222
#Sta/Elev= 30
8946.32932.939749018.22333.217539038.96531.242039142.67430.166079163.41631.83926
9184.15830.321819225.64232.026749267.12530.093019287.86732.614389308.609 30.1026
  9381.631.352149434.22229.26574 9455.2730.559339498.08828.47226 9585.4128.36132
9684.01830.118729786.52729.057989812.94327.61395 9850.6927.955719868.91130.05905
9923.497  30.5989980.83929.3508410021.1726.37043 10191.825.6234810331.9429.47966
10582.1832.4928310672.2735.7044910742.34 35.760110842.4539.2147310945.6739.63641
#Mann= 3 , 0 , 0
8946.329  0.0714       08946.329  0.0714       010945.67  0.0714       0
#XS Ineff= 2 , 0
       09929.913        10215.39       0
Bank Sta=8946.329,10945.67
Exp/Cntr=0.3,0.1

Type RM Length L Ch R = 1 , 7604.32,743.003300,743.003300,743.003300
XS GIS Cut Line= 4
924833.398637987801444.495974331924520.898637987800812.551529887
924305.620860209800736.162640998923586.870860209800923.662640998
#Sta/Elev= 30
9183.42422.111799316.73219.774779372.51221.097989472.91418.887719540.76620.37682
9573.31719.070379584.47320.894349595.62919.322659606.78520.580199631.005 17.9265
9698.68416.958149740.65519.307319796.43518.034149852.21419.400729885.682 19.0768
9937.11615.719059979.55917.4025210000.7815.4278410011.3917.3614710106.8919.16349
10189.8317.3492610251.8319.1673810324.1816.2528410406.8515.3918110437.8617.16537
 10479.215.9655610541.2118.5956610634.22 18.7497 10747.922.7828610859.6524.85298
#Mann= 3 , 0 , 0
9183.424  0.0949       09183.424  0.0949       010859.65  0.0949       0
#XS Ineff= 2 , 0
       09847.809        10443.88       0
Bank Sta=9183.424,10859.65
Exp/Cntr=0.3,0.1

Type RM Length L Ch R = 1 ,6861.317,917.722000,917.722000,917.722000
XS GIS Cut Line= 6
925361.176415765801392.412640998925218.815304654800902.829307664
924951.454193543800225.745974331924628.537526876800079.912640998
924326.454193543800097.273752109923319.509749098800503.523752109
#Sta/Elev= 30
8559.28613.59985 8760.4813.869728869.01710.608648900.25910.599538931.50213.37106
8983.57310.749479141.86811.569569246.1399.2481949273.87411.271989399.175 11.5225
9474.2229.3100389603.543 8.706349657.5429.1505829689.942 11.25129891.9978.575356
9968.804 10.314510056.588.37295410133.3910.4851810235.139.06142210385.3811.74229
 10510.19.85809810597.2711.6452710728.0210.3047710800.8612.3509910901.498.158585
11051.61 13.841311115.9513.3573811137.3914.7192911158.8412.5768211540.0320.47981
#Mann= 3 , 0 , 0
8559.286  0.0443       08559.286  0.0443       011540.03  0.0443       0
#XS Ineff= 2 , 0
       09610.737        10860.76       0
Bank Sta=8559.286,11540.03
Exp/Cntr=0.3,0.1