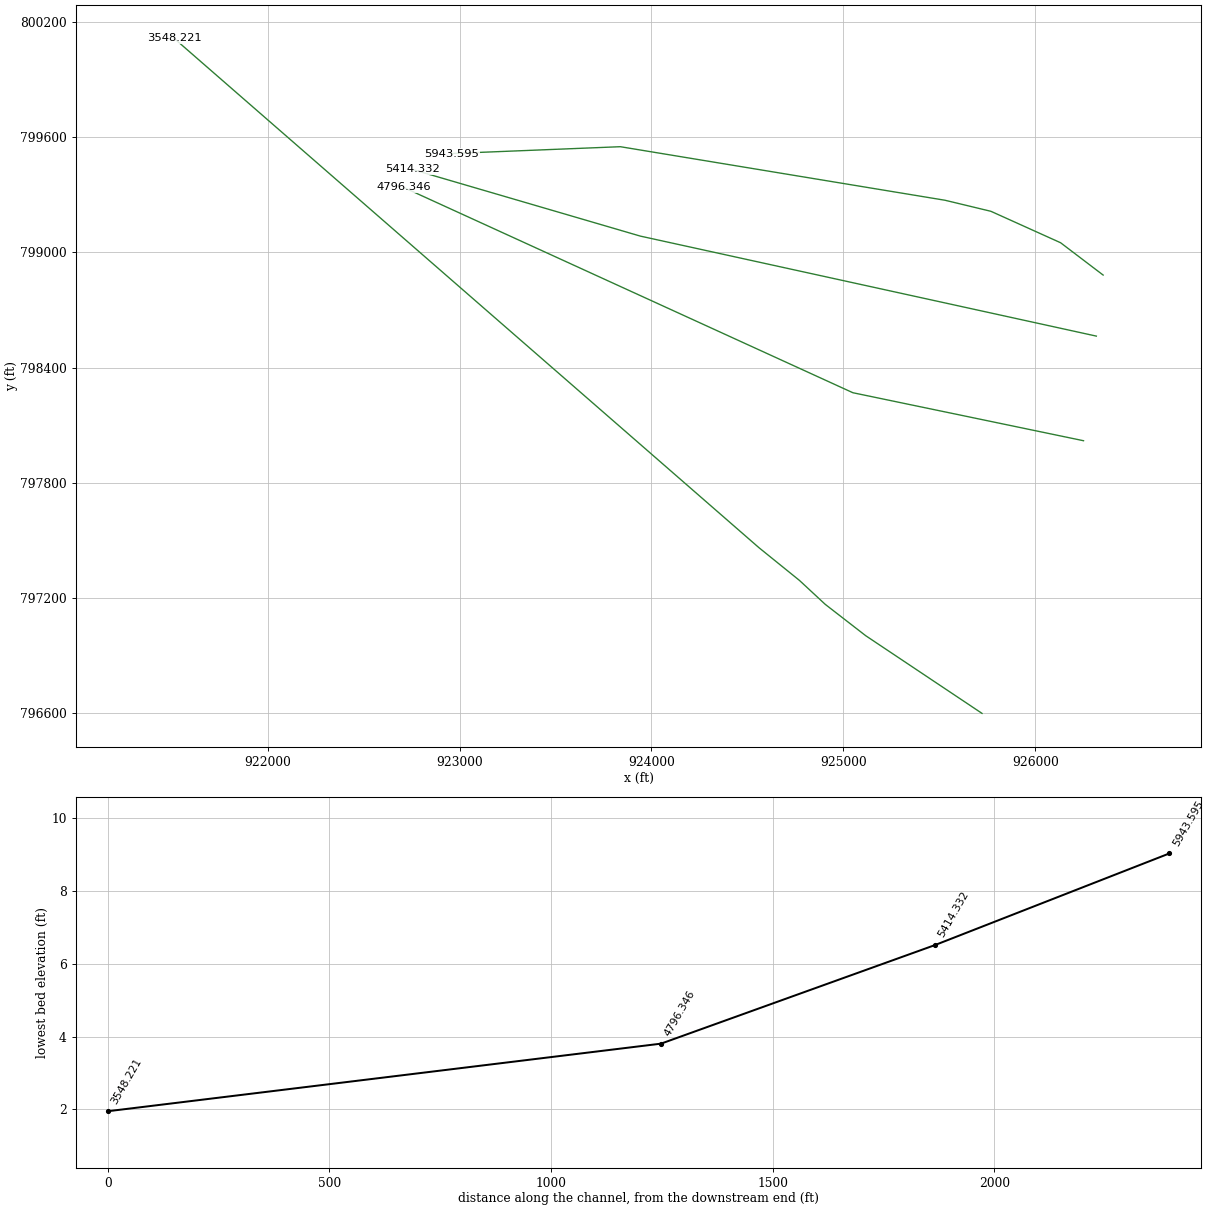
HEC-RAS study 13263_ras.prj: 13263

--- 13263_ras.g01 (geometry) --- (continued)

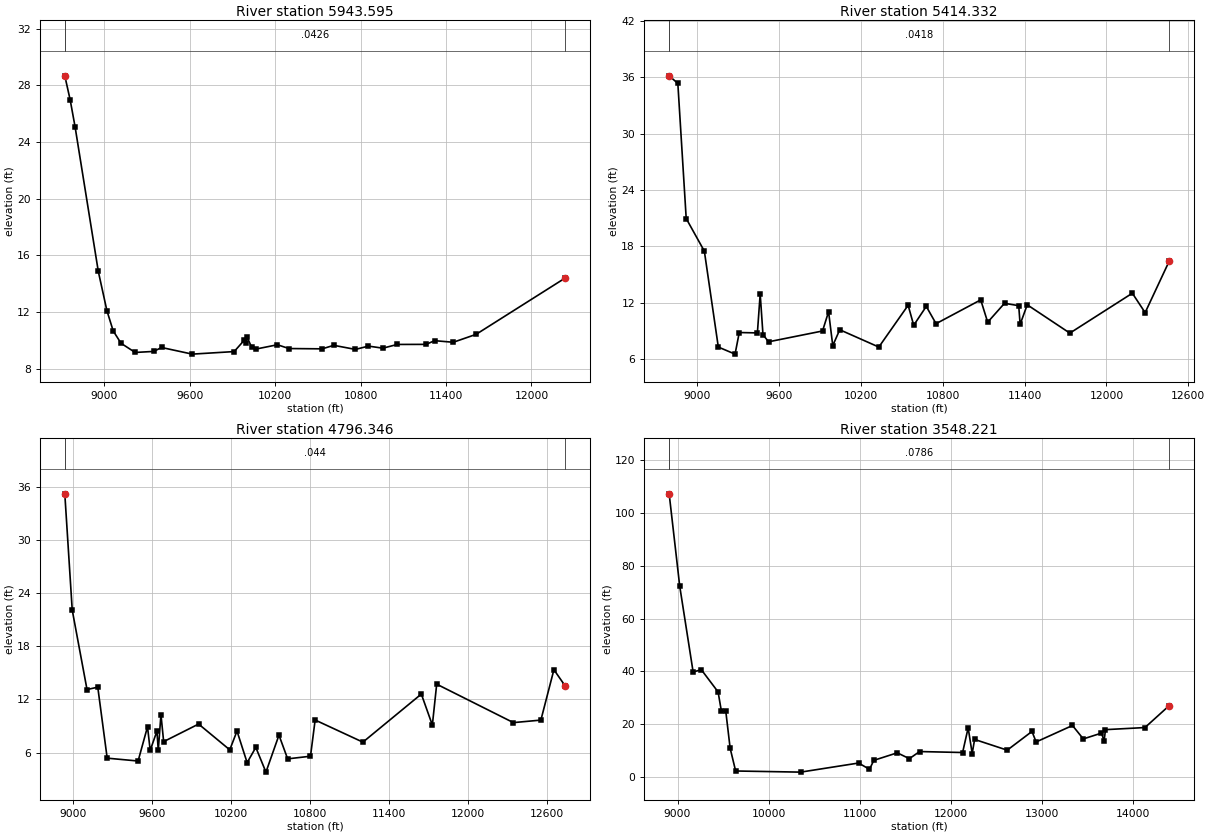
Type RM Length L Ch R = 1 ,5943.595,529.262700,529.262700,529.262700
XS GIS Cut Line= 6
926352.383637238798882.065765766926131.011986543799050.308220295
925767.962479401 799214.12324181 925528.88109665799271.679870991
923837.601685334799550.608150868922960.969948578799515.188686756
#Sta/Elev= 30
8721.36328.671028759.266 26.96458793.43925.083288956.72214.871849017.08212.10599
9061.22310.676499116.3999.8002699215.7179.1531249346.5019.2259829400.7969.504009
9616.7959.0347219911.2379.2145759982.00510.016749992.1399.82164410002.2710.22477
10034.779.50709110063.079.38972910215.089.69572510296.279.428745 10529.79.407406
 10610.9  9.655710763.139.36774310854.489.60099110955.979.45450511057.22  9.7182
 11259.49.72303111319.599.98406411450.549.87154211610.6710.4292112235.2114.39456
#Mann= 3 , 0 , 0
8721.363  0.0426       08721.363  0.0426       012235.21  0.0426       0
#XS Ineff= 2 , 0
       09423.291        11261.49       0
Bank Sta=8721.363,12235.21
Exp/Cntr=0.3,0.1

Type RM Length L Ch R = 1 ,5414.332,617.985700,617.985700,617.985700
XS GIS Cut Line= 3
 926317.14471002 798564.02194965 923942.14471002799084.855282984
 922754.64471002799432.077505206
#Sta/Elev= 30
8792.29236.163848855.91435.35609 8917.3420.959879050.42917.485869152.8057.269172
9275.6576.515316 9306.378.8172719439.459  8.77619459.93412.93517 9480.418.592362
 9521.367.8279929917.2658.9805619961.57811.036119992.291  7.419610043.489.113368
10330.137.26864410545.1211.7207210586.079.58990910678.2111.6000710749.889.758037
11077.4812.2952111128.679.91644511252.0111.93034 11356.2 11.677411366.629.686863
11418.7111.7709311731.278.753243 12189.713.0047312283.4610.9349612460.9516.44604
#Mann= 3 , 0 , 0
8792.292  0.0418       08792.292  0.0418       012460.95  0.0418       0
#XS Ineff= 2 , 0
       0                10987.37       0
Bank Sta=8792.292,12460.95
Exp/Cntr=0.3,0.1

Type RM Length L Ch R = 1 ,4796.346,1248.124900,1248.124900,1248.124900
XS GIS Cut Line= 3
926250.273714553798019.144688232925048.884825664798269.144688232
922708.607047886799338.589132677
#Sta/Elev= 30
8937.69135.174368994.14922.070979106.50513.115069188.21913.384469259.7195.381496
9494.6465.0594619566.1458.9197989586.5746.2534699637.6458.4344599647.8596.268484
9668.287 10.29829688.7167.2441639954.2859.22623710191.086.32068910246.058.436916
10323.01 4.8763110388.98 6.5936510465.943.80734810564.897.97662810630.865.302928
10804.465.59968610839.769.68068911202.58 7.1861911646.5512.6061611730.339.111298
11763.3113.7204812346.039.38838312554.939.67189512653.8815.3523212737.8713.55578
#Mann= 3 , 0 , 0
8937.691   0.044       08937.691   0.044       012737.87   0.044       0
#XS Ineff= 2 , 0
       0                10888.39       0
Bank Sta=8937.691,12737.87
Exp/Cntr=0.3,0.1

Type RM Length L Ch R = 1 ,3548.221,0.000000,0.000000,0.000000
XS GIS Cut Line= 6
925721.581293864796598.927720308925115.642710412797003.594810484
924905.210917014797166.680189174924770.392604744797291.718468309
924559.455068038 797462.20829214921513.389854227800115.074388311
#Sta/Elev= 30
8908.491107.11359024.62972.157739171.507 39.79249261.53740.660599445.50432.25583
9481.57925.008019529.67925.029479577.77910.986049637.9292.38024210351.61 1.95077
10987.795.38907411107.14  3.010711154.646.40243711412.149.24854311544.757.033346
11657.119.72701512129.139.36157712190.0318.7052912234.318.98883112260.8314.30498
12618.8710.2510712890.4417.3240412936.1213.3527313334.9619.5770913453.8214.49784
13653.2216.6982313682.2113.8142213697.4418.0043714130.6118.7968514397.9627.12078
#Mann= 3 , 0 , 0
8908.491  0.0786       08908.491  0.0786       014397.96  0.0786       0
#XS Ineff= 2 , 0
       0                10905.56       0
Bank Sta=8908.491,14397.96
Exp/Cntr=0.3,0.1